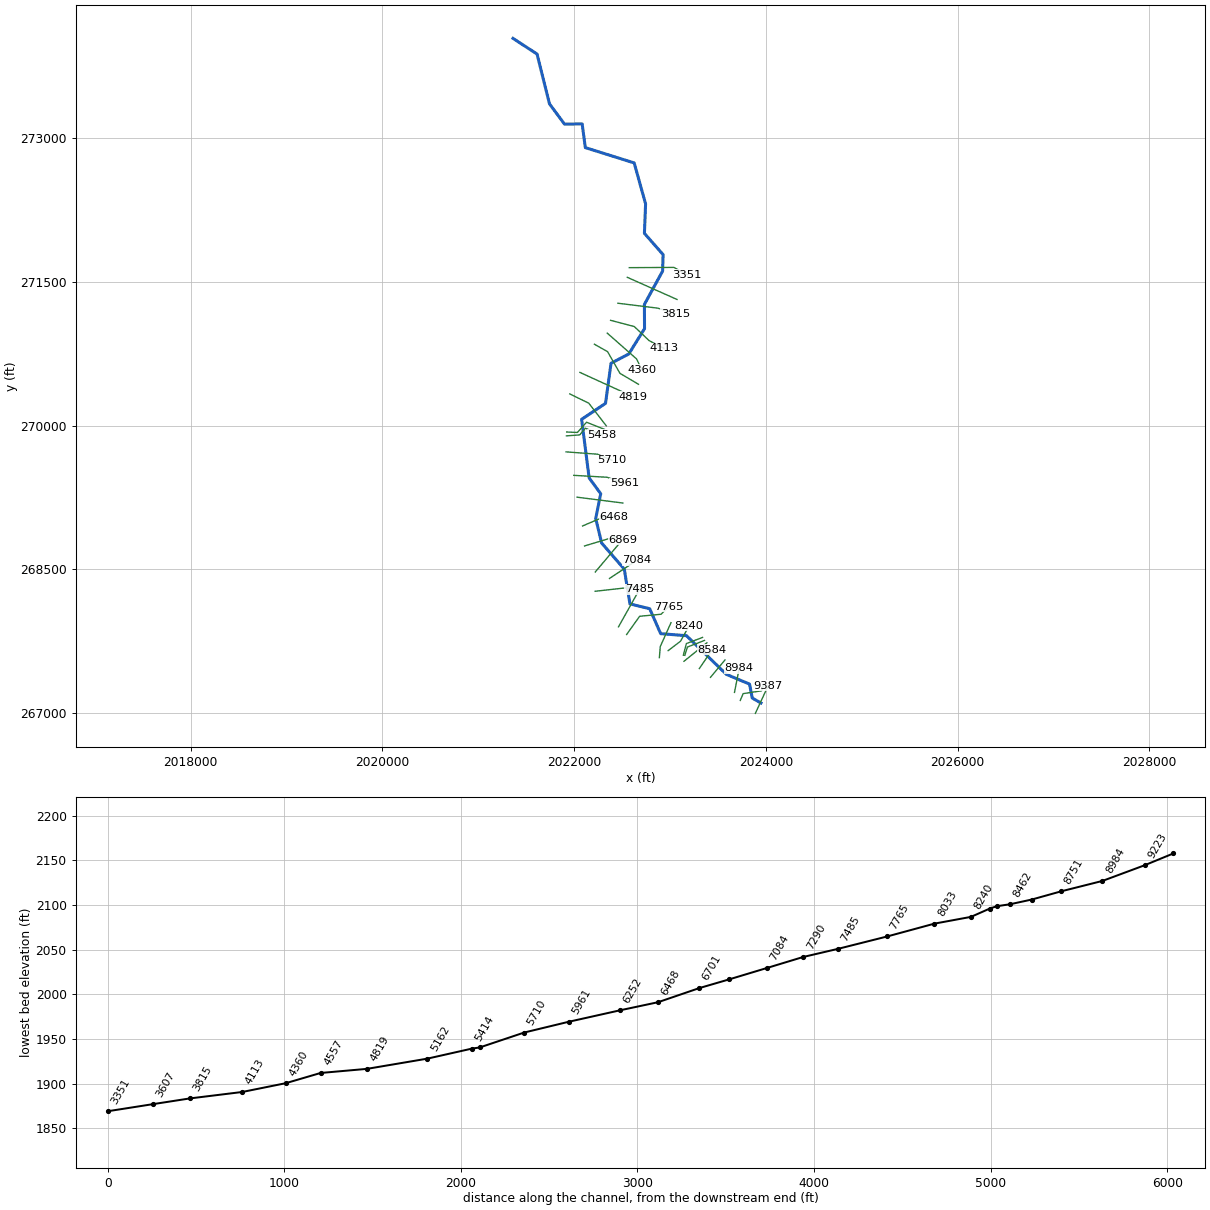
--- LAURELCK_T1.prj (project) ---

Proj Title=LAURELCK_T1
Current Plan=p01
Default Exp/Contr=0,0
English Units
Geom File=g01
Flow File=f01
Plan File=p01
BEGIN DESCRIPTION:
Stream Name: Laurel Creek Tributary 1
Flood Zone: Approximate
Summers County, West Virginia
HEC-RAS Version: 5.0.7
Hydrology Method:
regression
Model Notes:
coincident peak with LAURELCK_A
END DESCRIPTION:
DSS Export Rating Curves= 0
DSS Export Rating Curve Sorted= 0
DSS Export Volume Flow Curves= 0
DXF OffsetX= 0
DXF OffsetY= 0
DXF ScaleX= 0
DXF ScaleY= 0

--- LAURELCK_T1.p01 (plan) ---

Plan Title=Floodplain
Program Version=5.07
Short Identifier=Floodplain
Geom File=g01
Flow File=f01
Subcritical Flow
K Sum by GR= 0
Std Step Tol= 0.01
Critical Tol= 0.01
Num of Std Step Trials= 20
Max Error Tol= 0.3
Flow Tol Ratio= 0.001
Split Flow NTrial= 30
Split Flow Tol= 0.02
Split Flow Ratio= 0.02
Log Output Level= 0
Friction Slope Method= 1
Unsteady Friction Slope Method= 2
Unsteady Bridges Friction Slope Method= 1
Parabolic Critical Depth
Global Vel Dist= 0 , 0 , 0
Global Log Level= 0
CheckData=True
Encroach Param=-1 ,0,0, 0
Mapping Interval=1HOUR
Computation Time Step Use Courant=        0
Computation Time Step Use Time Series=    0
Computation Time Step Count To Double=0
Computation Time Step Max Doubling=0
Computation Time Step Max Halving=0
Computation Time Step Residence Courant=0
Run HTab= 0
Run UNet= 0
Run Sediment= 0
Run PostProcess= 0
Run WQNet= 0
Run RASMapper= 0
UNET Theta= 0
UNET Theta Warmup= 0
UNET ZTol= 0
UNET ZSATol= 0
UNET MxIter= 0
UNET Max Iter WO Improvement= 0
UNET MaxInSteps= 0
UNET DtIC= 0
UNET DtMin= 0
UNET MaxCRTS= 0
UNET WFStab= 0
UNET SFStab= 0
UNET WFX= 1
UNET SFX= 1
UNET 1D Methodology=Finite Difference
UNET DSS MLevel= 1
UNET Pardiso=0
UNET DZMax Abort= 0
UNET Use Existing IB Tables= 0
UNET Froude Reduction=False
UNET Froude Limit= 0
UNET Froude Power= 0
UNET D1 Cores= 0
UNET D2 Coriolis=0
UNET D2 Cores= 0
UNET D2 Theta= 1
UNET D2 Theta Warmup= 1
UNET D2 Z Tol= 0.01
UNET D2 Volume Tol= 0.01
UNET D2 Max Iterations= 20
UNET D2 Equation= 0
UNET D2 RampUpFraction=0.1
UNET D2 TimeSlices= 1
UNET D2 BCVolumeCheck=0
UNET D1D2 MaxIter= 0
UNET D1D2 ZTol=0.01
UNET D1D2 QTol=0.1
UNET D1D2 MinQTol=1
Write IC File= 0
Write IC File at Fixed DateTime=0
Write IC File at Sim End=0
Echo Input=False
Echo Parameters=False
Echo Output=False
Write Detailed= 0
HDF Write Warmup=0
HDF Write Time Slices=0
HDF Flush=0
HDF Face Node Velocities=0
HDF Compression= 1
HDF Chunk Size= 1
HDF Spatial Parts= 1
HDF Use Max Rows=0
HDF Fixed Rows= 1
Calibration Method= 0
Calibration Iterations= 20
Calibration Max Change=0.05
Calibration Tolerance=0.2
Calibration Maximum=1.5
Calibration Minimum=0.5
Calibration Optimization Method= 1
WQ AD Non Conservative
WQ ULTIMATE=-1
WQ Max Comp Step=1HOUR
WQ Output Interval=15MIN
WQ Output Selected Increments= 0
WQ Output face flow=0
WQ Output face velocity=0
WQ Output face area=0
WQ Output face dispersion=0
WQ Output cell volume=0
WQ Output cell surface area=0
WQ Output cell continuity=0
WQ Output cumulative cell continuity=0
WQ Output face conc=0
WQ Output face dconc_dx=0
WQ Output face courant=0
WQ Output face peclet=0
WQ Output face adv mass=0
WQ Output face disp mass=0
WQ Output cell mass=0
WQ Output cell source sink temp=0
WQ Output nsm pathways=0
WQ Output nsm derived pathways=0
WQ Output MaxMinRange=-1
WQ Daily Max Min Mean=-1
WQ Daily Range=0
WQ Daily Time=0
WQ Create Restart=0
WQ Fixed Restart=0
WQ System Summary=0
WQ Write To DSS=0
WQ Use Fixed Temperature=0
Sorting and Armoring Iterations= 10
XS Update Threshold= 0.02
Bed Roughness Predictor= 0
Hydraulics Update Threshold= 0.02
Energy Slope Method= 1
Volume Change Method= 1
Sediment Retention Method= 0
XS Weighting Method= 0
Number of US Weighted Cross Sections= 1
Number of DS Weighted Cross Sections= 1
Upstream XS Weight=0
Main XS Weight=1
Downstream XS Weight=0
Number of DS XS's Weighted with US Boundary= 1
Upstream Boundary Weight= 1
Weight of XSs Associated with US Boundary= 0
Number of US XS's Weighted with DS Boundary= 1
Downstream Boundary Weight= 0.5
Weight of XSs Associated with DS Boundary= 0.5
Percentile Method= 0
Sediment Output Level= 3
Mass or Volume Output= 0
Output Increment Type= 1
Profile and TS Output Increment= 1
XS Output Flag= 0
XS Output Increment= 10
Write Gradation File= 0
Read Gradation Hotstart= 0
Write HDF5 File= 1
Write Binary Output= 1
Write DSS Sediment File= 0
SV Curve= 0
Specific Gage Flag= 0

--- LAURELCK_T1.f01 (steady flow) ---

Flow Title=Flows
Program Version=5.07
Number of Profiles= 6
Profile Names=01pct,10pct,04pct,02pct,0_2pct,01plus
River Rch & RM=LAURELCK_T1,Main            ,9387
     532     280     373     450     744     787
River Rch & RM=LAURELCK_T1,Main            ,8584
     592     313     416     501     826     876
River Rch & RM=LAURELCK_T1,Main            ,6701
     819     439     579     695    1136    1211
River Rch & RM=LAURELCK_T1,Main            ,2525
     966     521     686     822    1336    1429
River Rch & RM=LAURELCK_T1,Main            ,0
    1881    1041    1353    1609    2569    2781
Boundary for River Rch & Prof#=LAURELCK_T1,Main            , 1
Up Type= 0
Dn Type= 1
Dn Known WS=1785.8
Boundary for River Rch & Prof#=LAURELCK_T1,Main            , 2
Up Type= 0
Dn Type= 1
Dn Known WS=1784.2
Boundary for River Rch & Prof#=LAURELCK_T1,Main            , 3
Up Type= 0
Dn Type= 1
Dn Known WS=1784.7
Boundary for River Rch & Prof#=LAURELCK_T1,Main            , 4
Up Type= 0
Dn Type= 1
Dn Known WS=1785.4
Boundary for River Rch & Prof#=LAURELCK_T1,Main            , 5
Up Type= 0
Dn Type= 1
Dn Known WS=1786.8
Boundary for River Rch & Prof#=LAURELCK_T1,Main            , 6
Up Type= 0
Dn Type= 1
Dn Known WS=1787
DSS Import GetInterval= 0
DSS Import GetPeak= 0
DSS Import FillOption= 0

--- LAURELCK_T1.g01 (geometry) ---

Geom Title=Geometry
Program Version=5.07

River Reach=LAURELCK_T1     ,Main
Reach XY= 30
2023948.83946665267106.577267186     2023858.809267157.671999915
2023830.00099999 267303.807999912023588.90099999267404.762999913
2023172.51499999267808.4359999182022903.36199999267829.536999916
2022788.77299999268089.8519999152022582.78599999268139.855999905
2022523.80599999268502.679999907     2022287.695268774.901999913
 2022225.8176624269030.4019794562022277.97199999269289.228999923
2022157.23638778 269454.070548382022078.76823638270064.951079566
2022327.94489855270231.4286554882022385.53799999270649.925999912
     2022570.595270746.6299999082022735.01399999271010.784999913
     2022733.484271263.4959999132022923.53935805271611.536729669
2022928.44208098271782.9452837922022733.70099999272004.936999917
2022745.95199999272312.038999912     2022626.931 272739.31199991
2022117.38199999 272899.03399991     2022084.396273146.429999916
2021900.36799999273143.825999917     2021743.941273354.884999913
2021613.90999999273874.7289999062021362.85339825274038.742884472

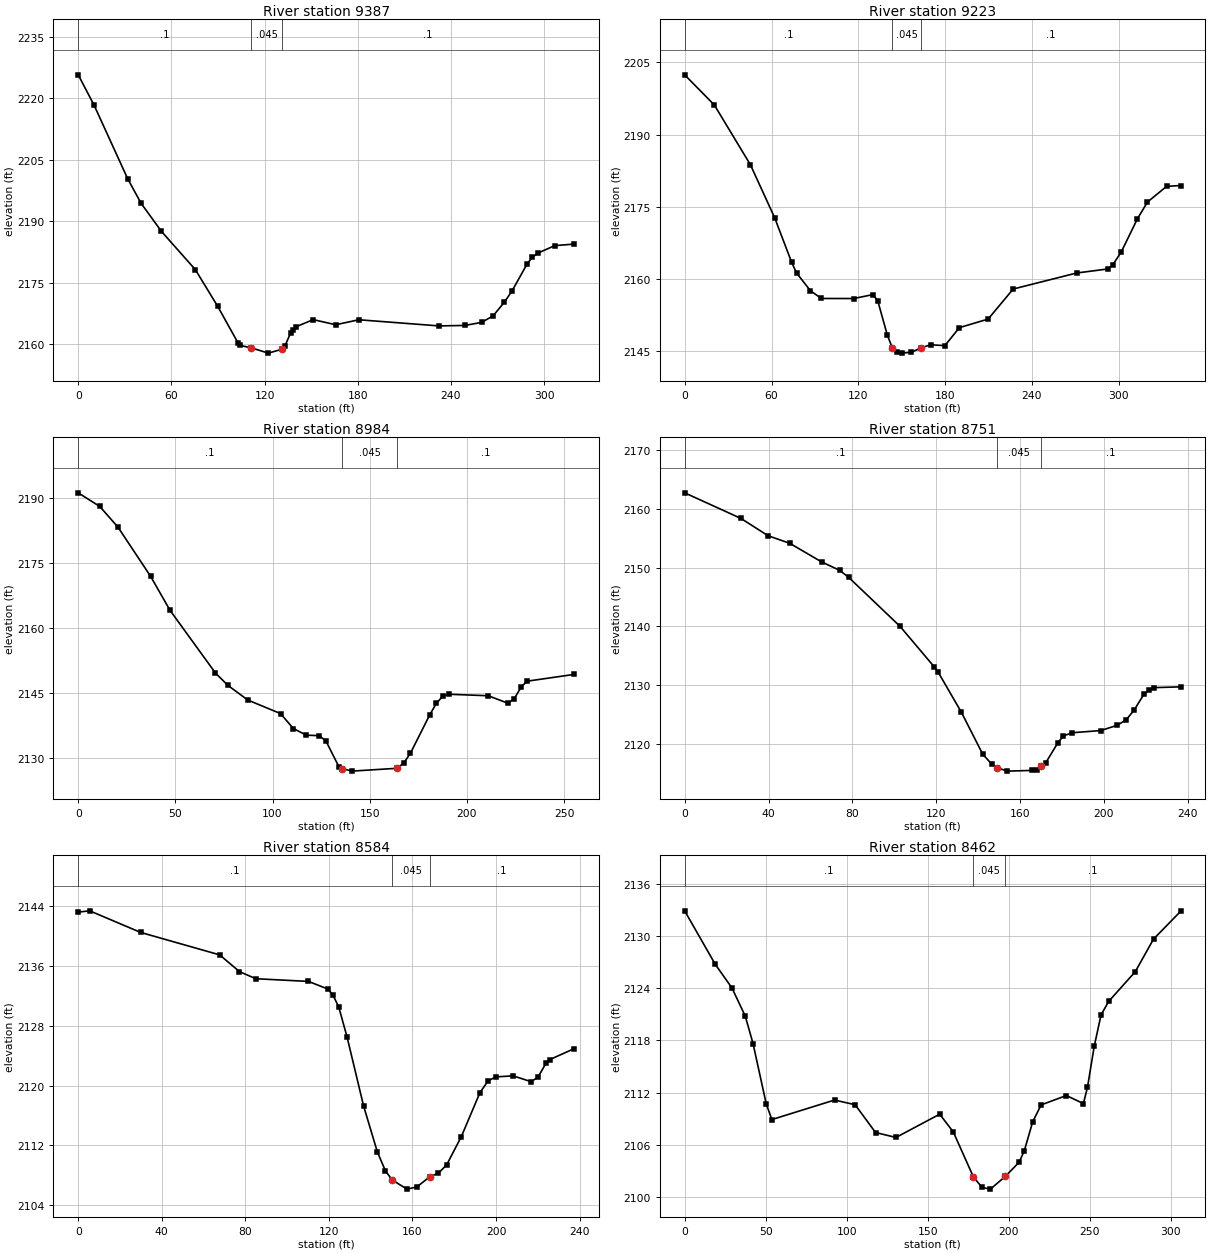
Type RM Length L Ch R = 1 ,9387    ,172.4,163.3,142.3
XS GIS Cut Line= 2
2023890.59125972266998.2911282372024025.02324199267287.880100525
#Sta/Elev= 30
       0 2225.69    10.2  2218.3    31.9 2200.29    40.5 2194.33    53.6 2187.48
    75.4 2178.16    89.8  2169.2   102.8 2160.34   104.3 2159.66   111.5 2159.06
   122.4 2157.78     131 2158.71   133.2 2159.61   136.8 2162.76   138.4 2163.53
   140.5 2164.26   151.3 2165.95   165.8 2164.71   180.7 2165.92   232.3 2164.42
     249 2164.54   259.8 2165.29   267.1 2166.87   274.3 2170.18   279.2 2172.89
   289.1  2179.6   292.4 2181.17     296  2182.2   306.8 2184.01   319.3 2184.39
#Mann= 3 ,-1 , 0
       0      .1       0   111.5    .045       0     131      .1       0
Bank Sta=111.5,131
XS Rating Curve= 0 ,0
Exp/Cntr=0.3,0.1

Type RM Length L Ch R = 1 ,9223    ,216,238.8,258.2
XS GIS Cut Line= 4
2023733.47072058267133.0651409612023763.63481727267204.267916205
2023954.96685184 267233.239328382023976.84265427267301.721009796
#Sta/Elev= 30
       0 2202.42    20.5 2196.14    45.4 2183.72    62.2 2172.67    73.9 2163.42
    77.3  2161.2    86.9 2157.49    94.5 2155.88   116.8 2155.87   130.1 2156.69
   133.4 2155.42     140 2148.29   143.4 2145.67   146.7 2144.74     150 2144.51
   156.6 2144.69   163.6 2145.63   169.9 2146.25   179.8 2146.07   189.8 2149.81
   209.7  2151.6     227 2157.85   270.8 2161.18   292.3 2162.02   295.7 2162.84
   301.6 2165.52   312.9 2172.49   319.8 2175.95     333 2179.21   342.7 2179.39
#Mann= 3 ,-1 , 0
       0      .1       0   143.4    .045       0   163.6      .1       0
Bank Sta=143.4,163.6
XS Rating Curve= 0 ,0
Exp/Cntr(USF)=0,0
Exp/Cntr=0.3,0.1

Type RM Length L Ch R = 1 ,8984    ,242.5,233.3,223.1
XS GIS Cut Line= 2
2023673.18794823267217.1527413312023722.29258405267467.606487343
#Sta/Elev= 30
       0 2191.28    11.1 2188.13    20.5 2183.32    37.2 2172.02    47.2 2164.16
    70.6 2149.65    77.1 2146.76    87.3 2143.39   104.1 2140.27   110.7 2136.81
   117.4 2135.28   124.1 2135.16   127.5 2133.91   134.1 2128.03   135.8 2127.57
   135.8 2127.56   140.8 2126.97   164.2 2127.63   167.6  2128.9   170.9 2131.06
   180.9 2139.99   184.3 2142.63   187.6  2144.3     191 2144.73     211 2144.39
   221.1 2142.66   224.4 2143.72     228 2146.47   231.1 2147.76   255.2 2149.32
#Mann= 3 ,-1 , 0
       0      .1       0   135.8    .045       0   164.2      .1       0
Bank Sta=135.8,164.2
XS Rating Curve= 0 ,0
Exp/Cntr=0.3,0.1

Type RM Length L Ch R = 1 ,8751    ,165.4,166.7,167.9
XS GIS Cut Line= 2
2023422.76149508267374.1081550962023574.40748063267555.671416419
#Sta/Elev= 30
       0 2162.74    26.9 2158.37    39.8 2155.43    50.1 2154.15    65.3 2150.98
    73.9 2149.55    78.2 2148.36   102.7 2140.02     119 2133.13   120.9 2132.22
     132 2125.38   142.2 2118.23   146.5 2116.53   149.2 2115.92   153.9 2115.35
   165.5 2115.47   167.9 2115.61   170.2 2116.19   172.2 2116.74   178.1 2120.21
   180.7 2121.36     185 2121.89   198.5 2122.26   206.4 2123.16   210.7 2124.11
   214.5 2125.79   219.1 2128.44   221.4 2129.13   224.1 2129.57   236.6  2129.7
#Mann= 3 ,-1 , 0
       0      .1       0   149.2    .045       0   170.2      .1       0
Bank Sta=149.2,170.2
XS Rating Curve= 0 ,0
Exp/Cntr=0.3,0.1

Type RM Length L Ch R = 1 ,8584    ,127.5,122.7,118.6
XS GIS Cut Line= 2
2023306.33152271267465.6118804442023440.25651567267661.668438116
#Sta/Elev= 30
       0  2143.2     5.5 2143.37    29.9 2140.48    67.7 2137.48    77.2 2135.24
      85 2134.29   110.2 2133.93   119.6  2132.9     122 2132.07   124.7 2130.52
   128.7 2126.49   136.6 2117.28   143.2 2111.12     147 2108.63   150.3 2107.37
   157.4 2106.15   162.1 2106.44   168.4 2107.83   172.4 2108.27   176.4 2109.41
   183.4 2113.18   192.3 2119.05   196.2 2120.63   199.9 2121.16   208.2  2121.3
   216.8 2120.52   220.1 2121.13   224.1 2123.08   225.8 2123.48   237.4 2124.94
#Mann= 3 ,-1 , 0
       0      .1       0   150.3    .045       0   168.4      .1       0
Bank Sta=150.3,168.4
XS Rating Curve= 0 ,0
Exp/Cntr=0.3,0.1

Type RM Length L Ch R = 1 ,8462    ,78.7,76,69.9
XS GIS Cut Line= 2
2023146.77740591 267541.82398907  2023384.775203267734.281442292
#Sta/Elev= 30
       0 2132.93    18.8 2126.79    29.2 2124.04    37.4  2120.8    42.2 2117.64
    50.3 2110.73    53.8 2108.89    92.5 2111.14   105.2  2110.6   117.8  2107.4
   130.4 2106.83   157.4 2109.51   165.8 2107.46   178.2 2102.29   183.5 2101.08
   188.7 2100.88   197.9 2102.35   206.4 2103.97   209.6 2105.29   214.8 2108.63
     220 2110.58   235.6 2111.66   246.1 2110.73   248.6  2112.6   252.8 2117.35
     257 2120.95   261.7  2122.5   278.1 2125.92   289.4 2129.68   306.1 2132.87
#Mann= 3 ,-1 , 0
       0      .1       0   178.2    .045       0   197.9      .1       0
Bank Sta=178.2,197.9
XS Rating Curve= 0 ,0
Exp/Cntr(USF)=0,0
Exp/Cntr=0.5,0.3

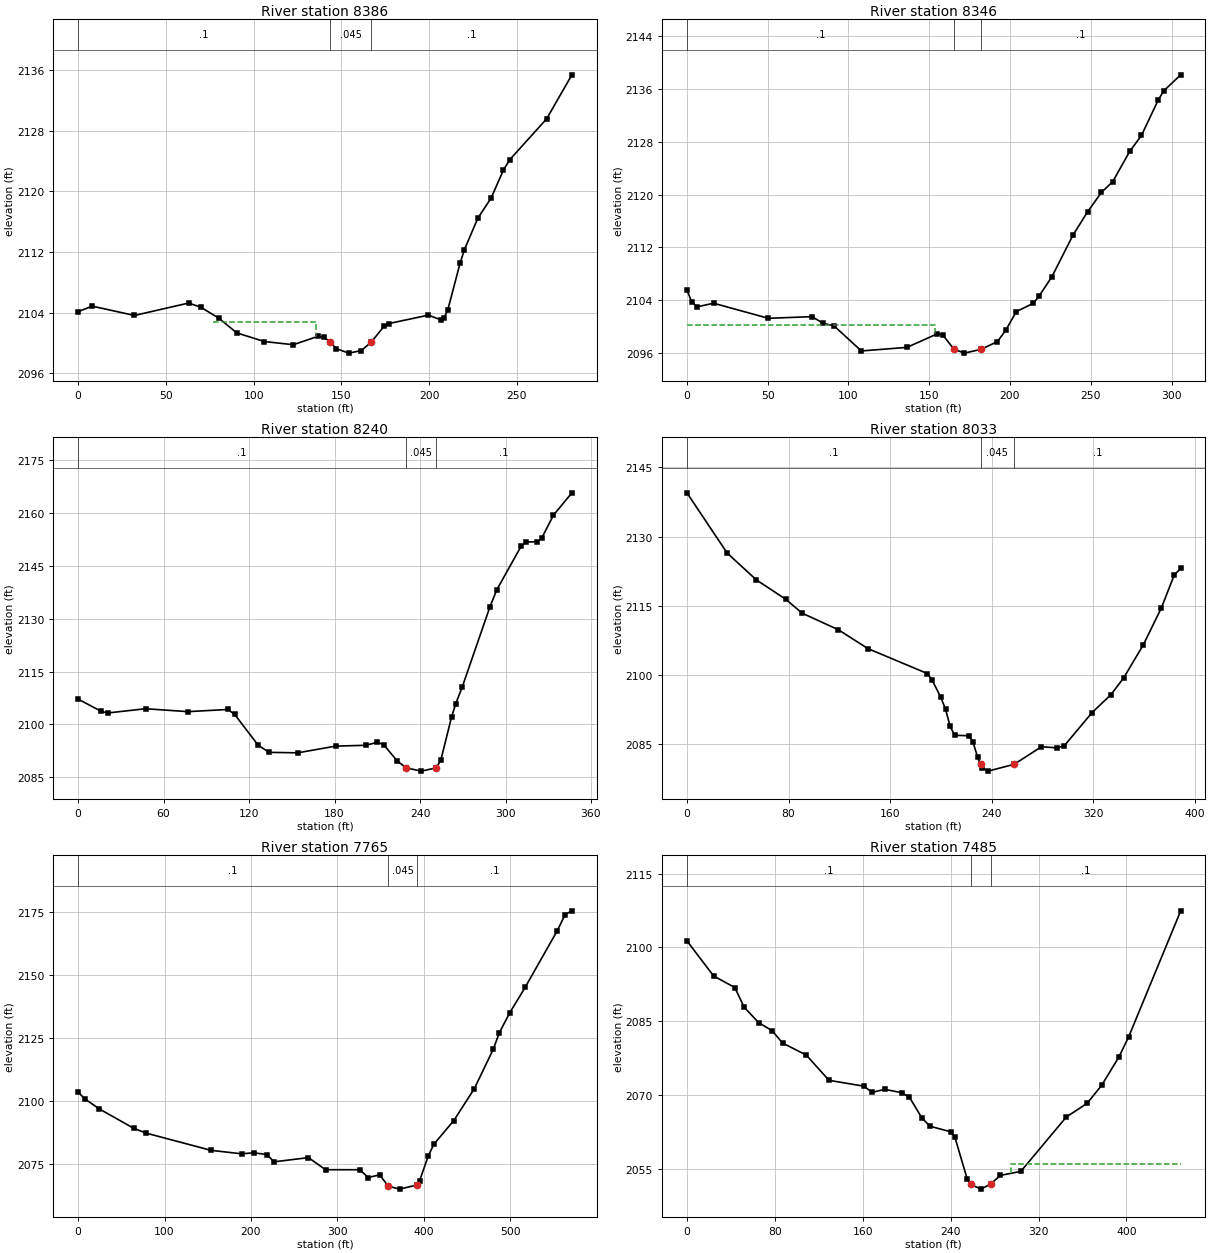
Type RM Length L Ch R = 1 ,8386    ,40.2,39.7,40.6
XS GIS Cut Line= 3
2023155.11446658267603.599444225 2023182.0954653267689.839659255
2023360.06844035267759.022763248
#Sta/Elev= 30
       0 2104.12       8 2104.85    32.1 2103.62      63 2105.26      70  2104.7
    80.2 2103.25    90.4 2101.32   106.1 2100.18   122.6 2099.76   136.6 2100.86
   140.2 2100.75   143.7 2100.08   147.2 2099.23   154.2 2098.65   161.3 2098.98
   166.9 2100.08   174.5 2102.25     177 2102.55   199.5 2103.66     207 2103.02
   208.5 2103.32   210.6 2104.35   217.6 2110.51   220.1 2112.32   227.7 2116.45
   235.2 2119.08   242.2 2122.75   245.8 2124.15   266.9 2129.56   281.3 2135.37
#Mann= 3 ,-1 , 0
       0      .1       0   143.7    .045       0   166.9      .1       0
#XS Ineff= 3 ,-1
  135.49     140  2097.4      77  135.49 2102.72     184   281.3  2101.2
Permanent Ineff=
       F       F       F
Bank Sta=143.7,166.9
XS Rating Curve= 0 ,0
Exp/Cntr(USF)=0,0
Exp/Cntr=0.5,0.3

Type RM Length L Ch R = 1 ,8346    ,96.5,106.3,116.3
XS GIS Cut Line= 3
2023139.85796921267605.1558053132023171.46778345267726.479127515
2023340.04487035267790.485170016
#Sta/Elev= 30
       0 2105.55     2.9 2103.79     6.3 2103.01    16.5 2103.55    50.4 2101.27
    77.5 2101.52    84.3 2100.51    91.1 2100.12     108 2096.33   136.2 2096.87
   154.8  2098.9   158.3 2098.78   165.3  2096.6   171.8    2096     182 2096.57
   192.2 2097.74   197.3 2099.43   203.9 2102.28   214.5 2103.55     218 2104.63
   225.9 2107.54     239 2113.86   248.1 2117.41   256.6 2120.32   263.6 2121.95
   274.1 2126.52   281.4 2128.95   291.7 2134.27   295.2  2135.7   305.7 2138.12
#Mann= 3 ,-1 , 0
       0      .1       0   165.3    .045       0     182      .1       0
#XS Ineff= 2 , 0
          153.73 2100.26
Permanent Ineff=
       F       F
Bank Sta=165.3,182
XS Rating Curve= 0 ,0
Exp/Cntr(USF)=0,0
Exp/Cntr=0.5,0.3

Type RM Length L Ch R = 1 ,8240    ,204.1,206.9,203.3
XS GIS Cut Line= 3
2022980.81129127267652.4291150462023110.17608145267750.820543733
2023200.24905926267911.326515847
#Sta/Elev= 30
       0 2107.18    16.3 2103.68    20.9 2103.24    47.4 2104.44    77.1 2103.61
   105.1 2104.23   109.9 2102.83   126.3 2094.12     134 2092.05   154.2 2091.92
   180.7 2093.82   201.9 2094.06   209.9 2094.88   214.4 2094.28     224  2089.6
   230.3 2087.64   240.9 2086.72   251.42087.653   254.6 2089.84   262.1 2102.03
     265 2105.78   269.6 2110.58   289.1 2133.41   293.9 2138.23     311 2150.61
   314.7 2151.79   322.3 2151.86   325.3  2152.8   333.6 2159.37   346.6 2165.75
#Mann= 3 ,-1 , 0
       0      .1       0   230.3    .045       0   251.4      .1       0
Bank Sta=230.3,251.4
XS Rating Curve= 0 ,0
Exp/Cntr(USF)=0,0
Exp/Cntr=0.3,0.1

Type RM Length L Ch R = 1 ,8033    ,283.8,267.4,242.6
XS GIS Cut Line= 3
2022889.68916562267579.7954735572022898.85039127267694.913924168
2023011.00523462267944.011362127
#Sta/Elev= 30
       0 2139.47    31.6 2126.44    54.6 2120.61    77.6 2116.43    90.8 2113.37
   119.3 2109.78   142.5  2105.7   189.2 2100.31   192.8 2098.99   199.8 2095.19
   203.6 2092.53   207.2 2088.84   210.8 2086.92   222.1 2086.82   225.2 2085.41
   228.8 2082.22   231.2  2080.6   232.4 2079.85     237 2079.15   257.6 2080.63
   279.1 2084.44   291.6 2084.18   297.2  2084.7   318.9 2091.83   333.8 2095.74
   343.7 2099.32   359.1 2106.44   373.5 2114.54   383.5 2121.59   388.7 2123.11
#Mann= 3 ,-1 , 0
       0      .1       0   231.2    .045       0   257.6      .1       0
Bank Sta=231.2,257.6
XS Rating Curve= 0 ,0
Exp/Cntr=0.3,0.1

Type RM Length L Ch R = 1 ,7765    ,256.3,280.5,299.8
XS GIS Cut Line= 4
2022548.15607145267820.9373277052022684.02166547268011.079937642
2022907.49378314268032.1009460772022987.43853621268112.148663201
#Sta/Elev= 30
       0  2103.4     8.1 2100.65    24.6 2096.72    64.2 2089.04    78.7  2087.1
   153.6 2080.25   189.2 2078.86   203.3 2079.27   218.1 2078.57   226.9 2075.68
   266.5 2077.34   286.3 2072.53   325.8 2072.52   335.7 2069.42   348.9  2070.5
   358.8 2065.99     372  2064.8   391.7 2066.42     395 2068.01   404.9 2077.79
   411.5 2082.62   434.6 2092.09   458.2 2104.65   480.4 2120.54   487.3 2127.03
   499.2 2134.87   517.2 2145.11   554.3 2167.63   563.5 2174.11   571.3 2175.59
#Mann= 3 ,-1 , 0
       0      .1       0   358.8    .045       0   391.7      .1       0
Bank Sta=358.8,391.7
XS Rating Curve= 0 ,0
Exp/Cntr=0.3,0.1

Type RM Length L Ch R = 1 ,7485    ,211.4,195.2,182.3
XS GIS Cut Line= 2
  2022463.163902267900.5498632572022683.02899846268292.443298792
#Sta/Elev= 30
       0 2101.34    24.3 2094.19    43.6 2091.85      52 2087.87    65.3  2084.7
    77.4 2083.09      87 2080.57   108.7 2078.09   129.3 2072.97   161.1 2071.78
   168.6 2070.52   179.9 2071.14   195.4 2070.46   202.5 2069.53   213.8 2065.33
   221.3 2063.63   240.1  2062.5   243.9 2061.38   255.1  2052.9   258.1  2051.8
   267.7 2050.84   276.8 2051.93   285.2 2053.63   303.9 2054.45   345.4 2065.54
   364.1 2068.27   377.4 2071.94   393.1  2077.7   401.9 2081.75   449.4 2107.45
#Mann= 3 ,-1 , 0
       0      .1       0   258.1    .045       0   276.8      .1       0
#XS Ineff= 2 , 0
                             295            2056
Permanent Ineff=
       F       F
Bank Sta=258.1,276.8
XS Rating Curve= 0 ,0
Exp/Cntr(USF)=0,0
Exp/Cntr=0.3,0.1

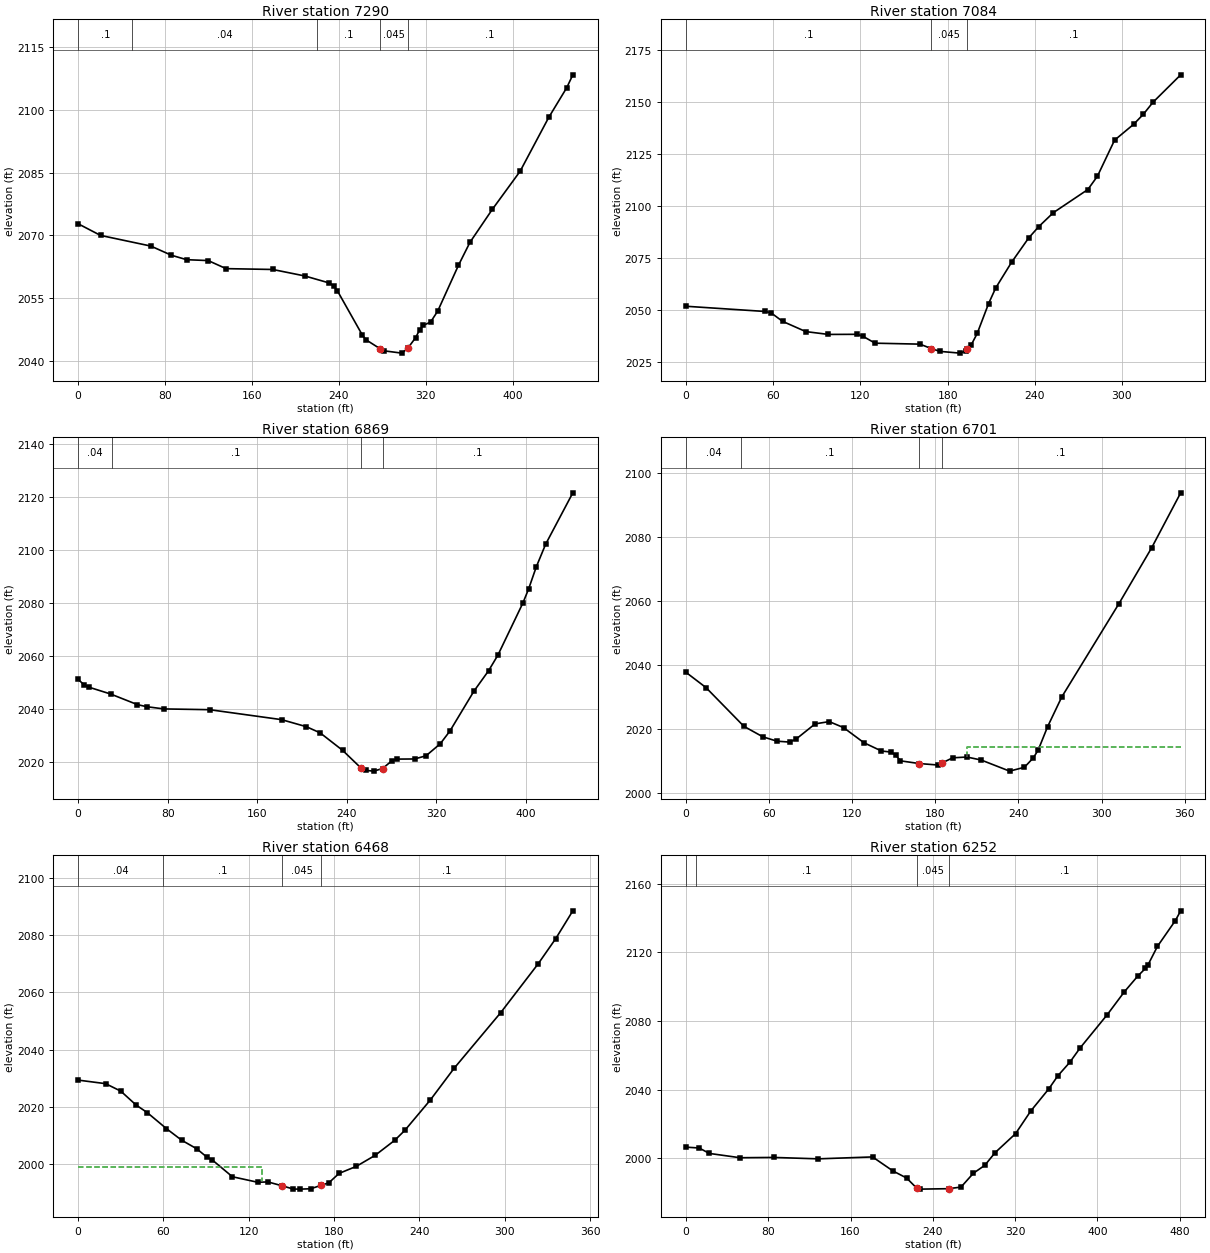
Type RM Length L Ch R = 1 ,7290    ,197.8,206.1,214.5
XS GIS Cut Line= 2
 2022220.4668548268271.8449106522022673.07617472268322.441480968
#Sta/Elev= 30
       0 2072.77    20.6 2069.99    66.9 2067.44    85.8 2065.25    99.9 2064.18
   119.7 2063.97   136.2 2062.04   179.1 2061.84   208.8 2060.28   231.3  2058.6
   235.2 2057.93   238.5 2056.81   261.6 2046.17   264.9 2045.04   278.1 2042.86
   281.4 2042.39   297.9 2041.83   303.3 2042.94   310.7 2045.54   314.4  2047.4
   317.8 2048.48   324.4 2049.25     331 2051.87   350.1 2062.83   360.7 2068.33
   381.3 2076.22   406.9 2085.34   433.2  2098.2   449.8 2105.32   455.4  2108.4
#Mann= 5 ,-1 , 0
       0      .1       0      50     .04       0     220      .1       0
   278.1    .045       0   303.3      .1       0
Bank Sta=278.1,303.3
XS Rating Curve= 0 ,0
Exp/Cntr(USF)=0,0
Exp/Cntr=0.3,0.1

Type RM Length L Ch R = 1 ,7084    ,209.2,214.4,218
XS GIS Cut Line= 2
 2022369.3593544268405.3882686192022652.86011471 268593.72330002
#Sta/Elev= 30
       0 2051.94    54.6 2049.43    58.6 2048.75    66.4 2044.72    82.4 2039.79
      98 2038.43   117.6 2038.48   121.6  2037.6   130.1 2034.23     161 2033.77
   168.9 2031.62   174.7  2030.3   188.5 2029.46   192.5 2030.48   193.6 2031.42
   196.4 2033.59   200.4 2038.93   208.2  2053.2   213.1 2060.71     224    2073
   235.8  2084.7   242.8 2090.18   252.8 2096.84   276.5 2107.92   283.1  2114.3
   294.9  2131.6     308  2139.2   314.6 2143.93   321.4 2149.82   340.4 2162.94
#Mann= 3 , 0 , 0
       0      .1       0   168.9    .045       0   193.6      .1       0
Bank Sta=168.9,193.6
XS Rating Curve= 0 ,0
Exp/Cntr(USF)=0,0
Exp/Cntr=0.3,0.1

Type RM Length L Ch R = 1 ,6869    ,177.8,168.4,162.5
XS GIS Cut Line= 2
2022221.14080219268472.9770079592022505.94656773268810.696449754
#Sta/Elev= 30
       0 2051.22     5.3  2049.2    10.1 2048.23    28.9 2045.74      53 2041.72
    61.3 2040.94    76.6 2040.11   117.4 2039.82   181.7 2036.07   203.8 2033.42
   216.1  2031.1   236.1 2024.54   252.4 2017.94     257 2016.95     264 2016.68
   271.9 2017.66   280.1 2020.55   284.7 2021.21   300.5 2021.26   310.7 2022.46
   323.4 2026.98     332 2031.76   353.4 2046.75   366.5 2054.45   374.9 2060.38
   397.2 2079.99   402.3 2085.27   409.2 2093.65   417.5 2102.12   441.8  2121.5
#Mann= 4 ,-1 , 0
       0     .04       0      30      .1       0   252.4    .045       0
   271.9      .1       0
Bank Sta=252.4,271.9
XS Rating Curve= 0 ,0
Exp/Cntr=0.3,0.1

Type RM Length L Ch R = 1 ,6701    ,230.2,233.1,236
XS GIS Cut Line= 2
2022109.11837265268744.5616101122022451.14198861268847.392239746
#Sta/Elev= 30
       0 2037.75    14.4 2033.01    41.8 2020.93    55.5 2017.65    65.7  2016.3
    74.8 2016.02    79.4 2016.93    93.2  2021.7   103.4  2022.4   113.7 2020.54
   128.4 2015.83   141.1 2013.24     148 2012.91   151.4 2011.94   154.8 2010.18
   168.2 2009.34   182.2 2008.86   184.62009.471   192.5 2011.12   202.8 2011.36
   213.1 2010.43   233.6 2006.97   244.3 2008.17   250.7  2011.1   254.2  2013.5
     261 2020.79   271.3 2030.12   312.4 2059.07   336.2  2076.6   357.1 2093.69
#Mann= 4 ,-1 , 0
       0     .04       0      40      .1       0   168.2    .045       0
   184.6      .1       0
#XS Ineff= 2 , 0
                          202.94          2014.5
Permanent Ineff=
       F       F
Bank Sta=168.2,184.6
XS Rating Curve= 0 ,0
Exp/Cntr(USF)=0,0
Exp/Cntr=0.3,0.1

Type RM Length L Ch R = 1 ,6468    ,224.2,215.8,204.6
XS GIS Cut Line= 3
2022088.74928167268952.9585258212022318.73369219269051.391853526
2022416.24708225269044.952290032
#Sta/Elev= 30
       0 2029.34    19.3  2028.1      30 2025.48    40.7 2020.64    48.6 2017.97
    62.1 2012.36    72.8 2008.31    83.5 2005.28    90.6 2002.36    94.2 2001.45
   108.5 1995.52   126.3 1993.59   133.5 1993.71   143.6 1992.33   151.3 1991.22
   156.1 1991.19   163.6 1991.32   171.1 1992.56   176.3  1993.4   183.5 1996.69
   195.6 1999.15   208.9 2003.02   222.7  2008.3   229.8 2011.78   247.7 2022.39
   264.3 2033.41   297.2 2052.96   323.5 2070.02   335.9 2078.87   347.9 2088.58
#Mann= 4 ,-1 , 0
       0     .04       0      60      .1       0   143.6    .045       0
   171.1      .1       0
#XS Ineff= 2 , 0
             129    1999
Permanent Ineff=
       F       F
Bank Sta=143.6,171.1
XS Rating Curve= 0 ,0
Exp/Cntr(USF)=0,0
Exp/Cntr=0.3,0.1

Type RM Length L Ch R = 1 ,6252    ,283.1,291.1,277.9
XS GIS Cut Line= 2
2022031.46879758269253.1685944112022508.61346529269192.177221739
#Sta/Elev= 30
       0 2006.55    12.8 2006.05    22.7 2002.89    52.5 2000.39    85.5 2000.56
   128.5 1999.74   181.4 2000.85   201.3 1992.66   214.5 1988.58   224.4 1982.63
   227.8 1982.11   255.41982.369   267.4 1983.31   279.5  1991.4   290.6    1996
   300.5 2003.33   320.4 2014.37   335.2 2027.57   352.8 2040.51   361.6 2048.11
   373.2 2055.96   383.2  2064.3   409.7 2083.75   426.2 2096.97   439.4 2106.23
   446.7 2110.58   449.4 2112.87   458.4 2123.44   475.8 2138.43     481 2144.13
#Mann= 4 ,-1 , 0
       0     .04       0      10      .1       0   224.4    .045       0
   255.4      .1       0
Bank Sta=224.4,255.4
XS Rating Curve= 0 ,0
Exp/Cntr=0.3,0.1

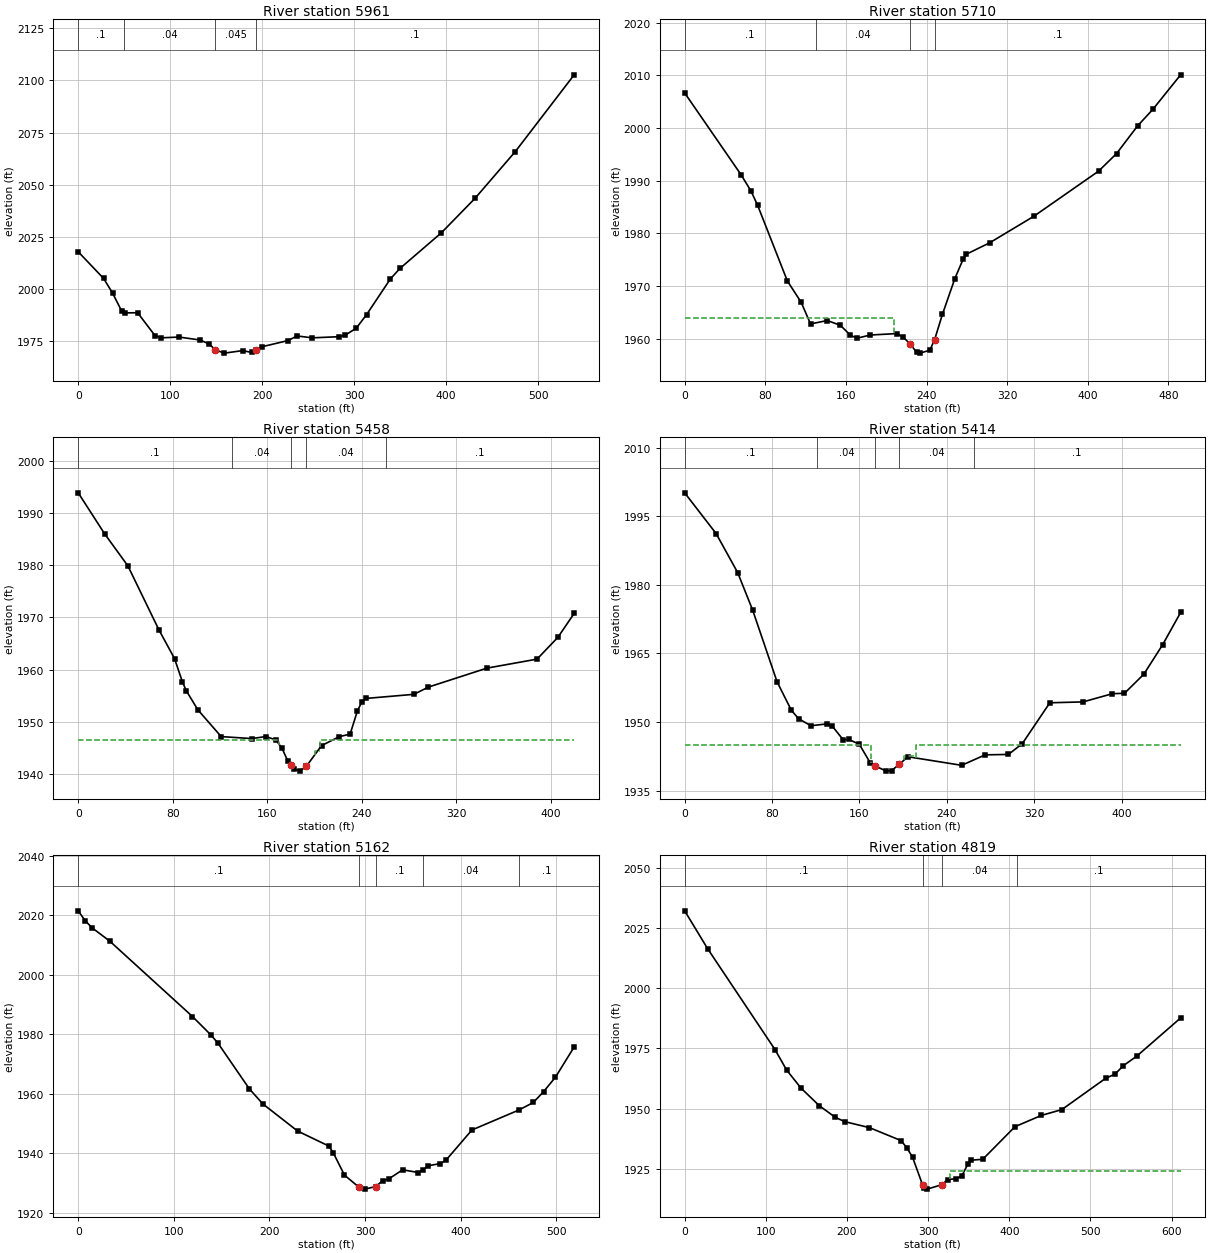
Type RM Length L Ch R = 1 ,5961    ,247.9,251.1,248.8
XS GIS Cut Line= 3
2021996.91781469269480.8926600092022345.41188381269460.764104262
2022524.79972402269398.208344599
#Sta/Elev= 30
       0 2017.84    27.6 2005.05    37.4 1997.99    47.3 1989.36    50.6 1988.54
    64.6 1988.61    83.4 1977.68      90 1976.58   109.7 1976.95   132.7 1975.53
   142.6 1973.54   149.2 1970.74     159 1969.25   178.7 1970.46   188.6 1969.58
   193.4 1970.57   199.6  1972.3     228 1975.26   237.9 1977.49   254.3 1976.58
   283.9 1977.13   290.5 1977.95   302.2 1981.17   313.5 1987.73   339.4 2004.86
   349.7 2009.84   394.8 2026.95   431.3 2043.44   475.1 2065.86   539.1 2102.67
#Mann= 4 ,-1 , 0
       0      .1       0      50     .04       0   149.2    .045       0
   193.4      .1       0
Bank Sta=149.2,193.4
XS Rating Curve= 0 ,0
Exp/Cntr(USF)=0,0
Exp/Cntr=0.3,0.1

Type RM Length L Ch R = 1 ,5710    ,237.8,251.8,265.9
XS GIS Cut Line= 3
2021916.26363765269725.6176076172022243.72693727269701.528142318
2022394.86233395269638.452412103
#Sta/Elev= 30
       0 2006.65    55.8 1991.16    65.7 1988.06    72.3 1985.35   101.9 1970.94
   115.5 1966.92   124.9 1962.78   141.4 1963.43   154.5 1962.53   164.4 1960.64
     171 1960.07   184.1 1960.68   210.5 1960.95     217 1960.25   223.51959.011
   230.2  1957.4   233.5 1957.24   243.3  1957.8     2481959.796   255.7 1964.58
   268.1 1971.41   276.2 1975.04   279.5 1976.02   302.6 1978.19   346.4 1983.22
   410.7  1991.8   428.5 1995.13   449.4 2000.39   464.5 2003.52   492.1 2010.09
#Mann= 4 ,-1 , 0
       0      .1       0     130     .04       0   223.5    .045       0
     248      .1       0
#XS Ineff= 2 , 0
             208    1964
Permanent Ineff=
       F       F
Bank Sta=223.5,248
XS Rating Curve= 0 ,0
Exp/Cntr(USF)=0,0
Exp/Cntr=0.5,0.3

Type RM Length L Ch R = 1 ,5458    ,42.2,44.6,47.2
XS GIS Cut Line= 4
2021920.17181055269892.8282430562022058.82391923269902.396848641
2022117.22235927269972.3889664732022293.08223129269901.675677763
#Sta/Elev= 30
       0 1993.82    22.3 1985.99      42 1979.85    68.3 1967.59    81.5  1962.1
    88.1 1957.69    91.4 1955.96   101.2  1952.3     121 1947.16   146.8 1946.78
   158.9 1947.17   167.3 1946.51   172.4 1944.95   177.5 1942.44   180.3 1941.63
   182.6 1940.97   187.7 1940.55   193.1 1941.49   205.9 1945.43   220.9 1947.15
   230.1 1947.63   236.3 1952.09   239.8  1953.7   243.3 1954.46   284.1 1955.25
   296.3 1956.63   345.8 1960.26   388.3 1961.99     406 1966.18   419.7 1970.74
#Mann= 5 ,-1 , 0
       0      .1       0     130     .04       0   180.3    .045       0
   193.1     .04       0  260.14      .1       0
#XS Ineff= 3 ,-1
       0   170.3  1946.5     200     205  1944.4     205  419.68  1946.5
Permanent Ineff=
       F       F       F
Bank Sta=180.3,193.1
XS Rating Curve= 0 ,0
Exp/Cntr(USF)=0,0
Exp/Cntr=0.5,0.3

Type RM Length L Ch R = 1 ,5414    ,273.8,251.9,222.8
XS GIS Cut Line= 4
2021923.51197899269932.7093293782022034.79935757269928.076094393
2022130.22602875270034.9488816232022315.39050838269961.398958355
#Sta/Elev= 30
       0 2000.11    28.8 1991.19    48.5 1982.67    62.3  1974.4    84.6 1958.75
    97.7 1952.52   104.3  1950.7   115.5 1949.17   130.3 1949.57   135.2 1949.05
   145.1 1946.08   150.1  1946.2   159.9 1945.09   169.7 1941.11   174.6 1940.34
   184.5 1939.24   189.4 1939.37   196.6 1940.76   204.2 1942.39   253.5 1940.51
     275  1942.8   296.3 1942.89     309 1945.25   334.2 1954.19   364.6 1954.38
   391.5 1956.18   402.5 1956.26   420.2 1960.43   437.4 1966.87   453.9 1973.94
#Mann= 5 ,-1 , 0
       0      .1       0  121.38     .04       0   174.6    .045       0
   196.6     .04       0  264.66      .1       0
#XS Ineff= 3 ,-1
       0   170.6    1945   200.6     212  1942.5     212   453.9    1945
Permanent Ineff=
       F       F       F
Bank Sta=174.6,196.6
XS Rating Curve= 0 ,0
Exp/Cntr(USF)=0,0
Exp/Cntr=0.5,0.3

Type RM Length L Ch R = 1 ,5162    ,334,342.5,347.1
XS GIS Cut Line= 3
2021955.51411276270330.0908774462022153.13034699  270233.5542113
2022335.98214993269997.323310612
#Sta/Elev= 30
       0 2021.46     7.3 2018.14    14.6 2015.73    32.9 2011.31   119.5 1985.98
   138.8 1979.78   146.1 1977.06     179 1961.68   193.1 1956.63   229.4 1947.53
   262.2 1942.47     267 1940.07   278.5 1932.71   293.8 1928.63   299.6 1928.02
   311.3 1928.89   318.3 1930.85   324.8 1931.45   339.3 1934.51   355.7  1933.6
   360.4 1934.43   366.3 1935.89   378.7 1936.59   384.9 1937.84   411.8 1947.88
   460.9 1954.58     476 1957.11   486.7 1960.74   499.1 1965.58   518.7 1975.75
#Mann= 5 ,-1 , 0
       0      .1       0   293.8    .045       0   311.3      .1       0
   360.4     .04       0   460.9      .1       0
Bank Sta=293.8,311.3
XS Rating Curve= 0 ,0
Exp/Cntr(USF)=0,0
Exp/Cntr=0.3,0.1

Type RM Length L Ch R = 1 ,4819    ,280.3,262.3,248.1
XS GIS Cut Line= 2
2022060.98394066270554.4682551532022616.93223392270300.788197064
#Sta/Elev= 30
       0 2032.08    28.4 2016.29   111.3 1974.48   125.7 1965.95   143.5 1958.44
   165.8 1951.22   185.6 1946.34   197.4 1944.56   227.7 1942.08   266.4 1936.74
   273.6 1933.82   280.8  1929.8   293.2 1918.26   295.2 1917.07   298.8 1916.56
   316.9 1918.41   324.1 1920.54   334.9  1920.9   341.6 1922.11   349.3 1927.18
   352.9 1928.57   367.3 1928.94     407 1942.48   439.5 1947.16   464.7 1949.56
   518.8 1962.58   530.3 1964.29   540.4 1967.77   557.1 1971.77   611.1 1987.61
#Mann= 4 ,-1 , 0
       0      .1       0   293.2    .045       0   316.9     .04       0
     410      .1       0
#XS Ineff= 2 , 0
                             327            1924
Permanent Ineff=
       F       F
Bank Sta=293.2,316.9
XS Rating Curve= 0 ,0
Exp/Cntr=0.3,0.1

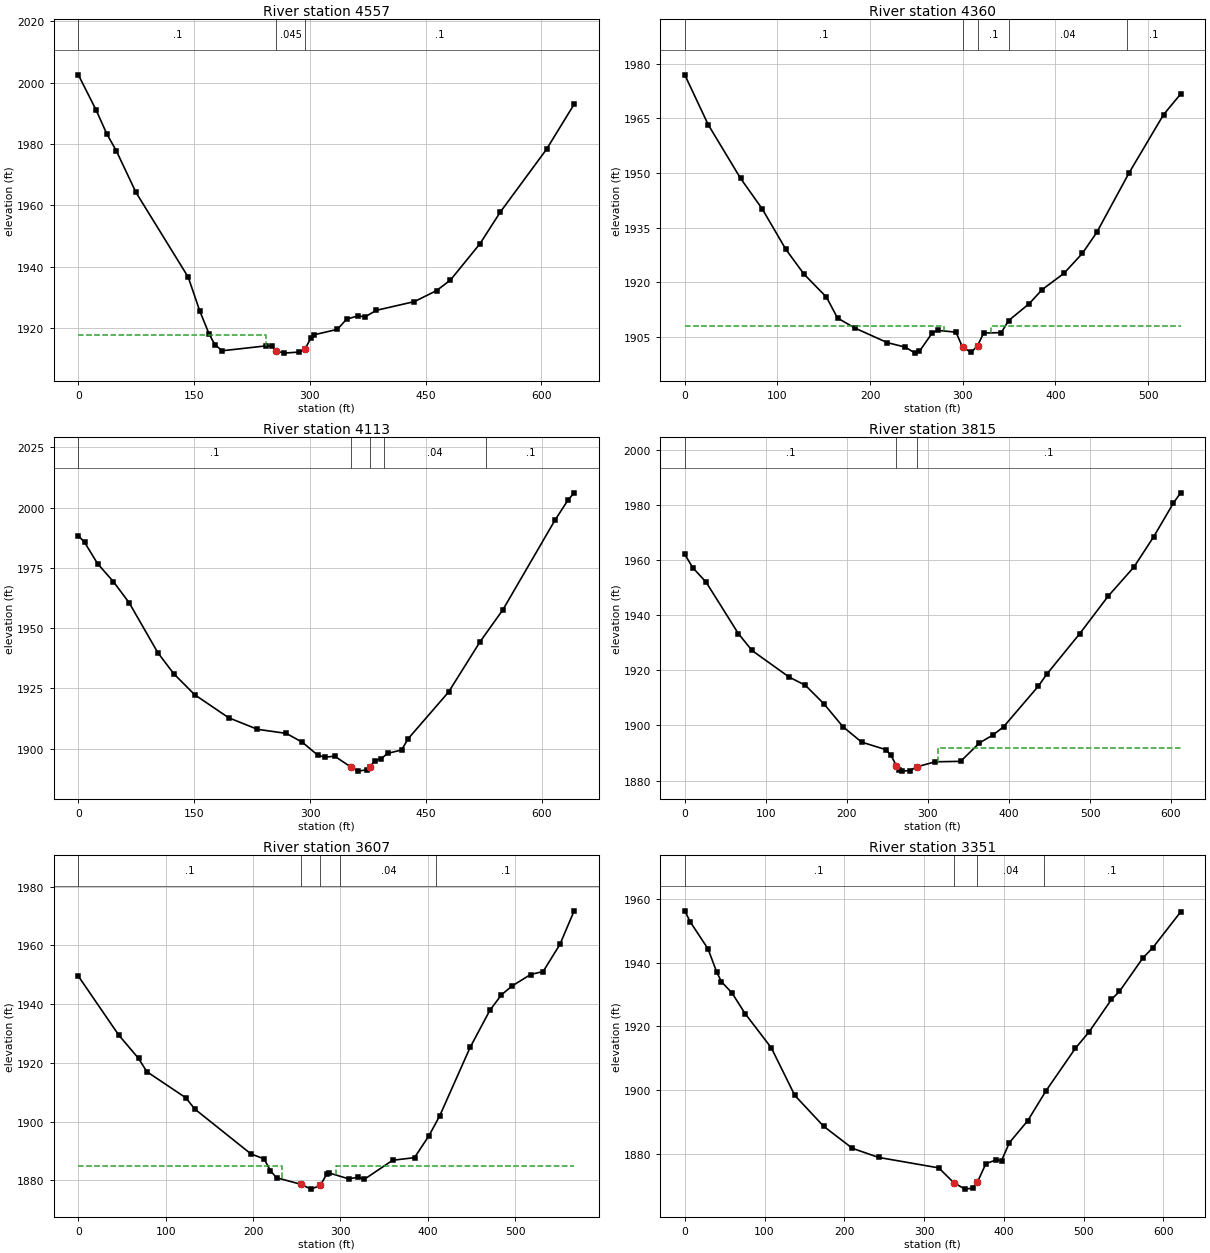
Type RM Length L Ch R = 1 ,4557    ,192.3,197.2,200.4
XS GIS Cut Line= 4
2022212.12817645270848.3383538412022349.61085574270770.752365268
2022478.58252904270544.7523732042022671.80825546270430.704391943
#Sta/Elev= 30
       0 2002.51    22.8 1991.18    36.9 1983.28    49.3 1977.75    74.6 1964.29
   142.4 1936.67   157.4 1925.64   169.3 1918.28   176.8 1914.74   186.5 1912.74
   243.2 1914.33   251.4 1914.13   256.4 1912.74   265.9 1911.97   286.4 1912.32
   293.9 1913.36   301.5 1917.03   305.2 1917.92   335.5  1919.7   347.6 1923.01
   361.9 1924.07   371.7  1923.8   386.1 1925.89   435.5 1928.74   464.1 1932.31
   482.1 1935.74   520.4 1947.57   546.7 1957.86   606.6 1978.29   642.4 1992.95
#Mann= 3 ,-1 , 0
       0      .1       0   256.4    .045       0   293.9      .1       0
#XS Ineff= 2 , 0
             243    1918
Permanent Ineff=
       F       F
Bank Sta=256.4,293.9
XS Rating Curve= 0 ,0
Exp/Cntr=0.3,0.1

Type RM Length L Ch R = 1 ,4360    ,246.3,246.7,243.8
XS GIS Cut Line= 3
2022345.99721518270963.9839612742022651.62498001270695.233196439
 2022708.5979619270580.509019363
#Sta/Elev= 30
       0 1976.96    25.3 1963.25    60.2 1948.52    83.5 1940.16     109 1929.05
   128.7 1922.21   152.9  1915.9   164.8 1910.17   183.4 1907.44   218.4 1903.43
   238.1 1902.16   248.5 1900.53   253.2 1901.03   267.1 1906.09   272.8 1906.79
   292.7 1906.28   299.7 1902.17     309 1900.75   315.9 1902.53   322.5 1906.05
   341.5 1906.16   349.5 1909.47   371.7 1914.12   385.7 1917.99     409  1922.4
     429  1927.9   444.6 1933.69   479.5 1950.05   516.7 1966.03   535.1 1971.69
#Mann= 5 ,-1 , 0
       0      .1       0   299.7    .045       0   315.9      .1       0
     350     .04       0  476.98      .1       0
#XS Ineff= 2 , 0
             280    1908     330            1908
Permanent Ineff=
       F       F
Bank Sta=299.7,315.9
XS Rating Curve= 0 ,0
Exp/Cntr=0.3,0.1

Type RM Length L Ch R = 1 ,4113    ,288.5,297.8,310.6
XS GIS Cut Line= 4
2022380.85794145271097.8116614672022628.24123627271032.690170525
2022782.36542274270886.2363396662022936.29215788270805.841307627
#Sta/Elev= 30
       0 1988.27       8 1985.63      25 1976.69    45.3  1969.3    65.7 1960.57
     103 1939.78   123.4 1931.14   150.5 1922.41   194.6 1912.83   231.9 1908.03
   269.3 1906.33   290.2 1902.64   309.9 1897.33     319 1896.46     332 1896.87
   352.9  1892.4   362.1 1890.68   373.3  1891.2   377.8 1892.35   383.7    1895
   392.3 1895.86   400.5 1898.05   418.6 1899.43   427.1 1904.11   479.5 1923.49
   520.2 1944.32   549.8  1957.6   617.2 1994.72   634.2 2003.14   642.1  2006.1
#Mann= 5 ,-1 , 0
       0      .1       0   352.9    .045       0   377.8      .1       0
  395.81     .04       0  528.42      .1       0
Bank Sta=352.9,377.8
XS Rating Curve= 0 ,0
Exp/Cntr=0.3,0.1

Type RM Length L Ch R = 1 ,3815    ,213.4,207.9,203.1
XS GIS Cut Line= 3
2022457.56177912271275.9207463712022874.00701128  271224.4919015
2023056.96181884271165.516937732
#Sta/Elev= 30
       0 1962.03     9.9 1957.24    26.4 1951.94    66.1 1933.32    82.9 1927.21
   128.9 1917.53   148.7  1914.6   171.8 1907.82     195 1899.59   218.1 1893.98
   247.9 1891.24   254.5 1889.16   261.1 1885.34   264.4 1883.81   267.7 1883.44
   277.6 1883.63   286.6 1885.02   308.9 1886.82   340.4 1886.99   363.6 1893.69
   380.1 1896.51   393.3 1899.51   436.2 1914.25   446.6  1918.6   487.2 1933.26
   522.2 1946.84   554.2 1957.49   578.4 1968.39     603 1980.73   611.8  1984.4
#Mann= 3 ,-1 , 0
       0      .1       0   261.1    .045       0   286.6      .1       0
#XS Ineff= 2 , 0
                             312            1892
Permanent Ineff=
       F       F
Bank Sta=261.1,286.6
XS Rating Curve= 0 ,0
Exp/Cntr=0.3,0.1

Type RM Length L Ch R = 1 ,3607    ,244.3,255.8,262.7
XS GIS Cut Line= 2
2022555.32400504271546.145682388 2023073.9719761271315.214833959
#Sta/Elev= 30
       0 1949.58    46.1 1929.57    68.9 1921.58    78.4 1917.05   122.8 1908.21
   133.6 1904.26   197.7 1889.03   212.6 1887.38     220  1883.3   226.9 1880.94
   254.8 1878.71   266.4 1877.06   277.1  1878.3   284.4  1882.2   287.1 1882.57
   309.4 1880.57   320.3 1881.08   327.5 1880.41   359.8 1886.88   384.9 1887.78
   401.4 1895.21   413.7 1901.96   448.6 1925.31   471.1 1937.88   484.4 1943.18
   496.3 1946.15   517.8 1950.12   532.2 1951.14   551.4 1960.37   567.7  1971.8
#Mann= 5 ,-1 , 0
       0      .1       0   254.8    .045       0   277.1      .1       0
     300     .04       0     410      .1       0
#XS Ineff= 2 , 0
             233    1885     295            1885
Permanent Ineff=
       F       F
Bank Sta=254.8,277.1
XS Rating Curve= 0 ,0
Exp/Cntr(USF)=0,0
Exp/Cntr=0.3,0.1

Type RM Length L Ch R = 1 ,3351    ,186.7,194.9,200.5
XS GIS Cut Line= 3
2022575.51468031 271647.099058752023041.16212879271649.622893159
2023177.44918688271573.907860888
#Sta/Elev= 30
       0 1956.16     6.7 1952.75    29.1 1944.27    40.1 1936.94      46 1933.98
    59.2 1930.46    75.6 1924.02   108.4 1913.34   137.9 1898.44     174  1888.8
   210.1 1881.89   242.9 1879.05   318.4 1875.77     337 1871.18   351.2 1869.13
     361 1869.43   366.7 1871.23   377.4 1877.07   390.5  1878.3   397.1 1878.02
   406.9 1883.64   429.9 1890.52   452.9  1899.9   489.8 1913.22   506.7 1918.25
   534.9 1928.45   544.9 1930.95   574.2 1941.39   586.6 1944.58   621.6 1955.81
#Mann= 4 ,-1 , 0
       0      .1       0     337    .045       0   366.7     .04       0
     450      .1       0
Bank Sta=337,366.7
XS Rating Curve= 0 ,0
Exp/Cntr(USF)=0,0
Exp/Cntr=0.3,0.1