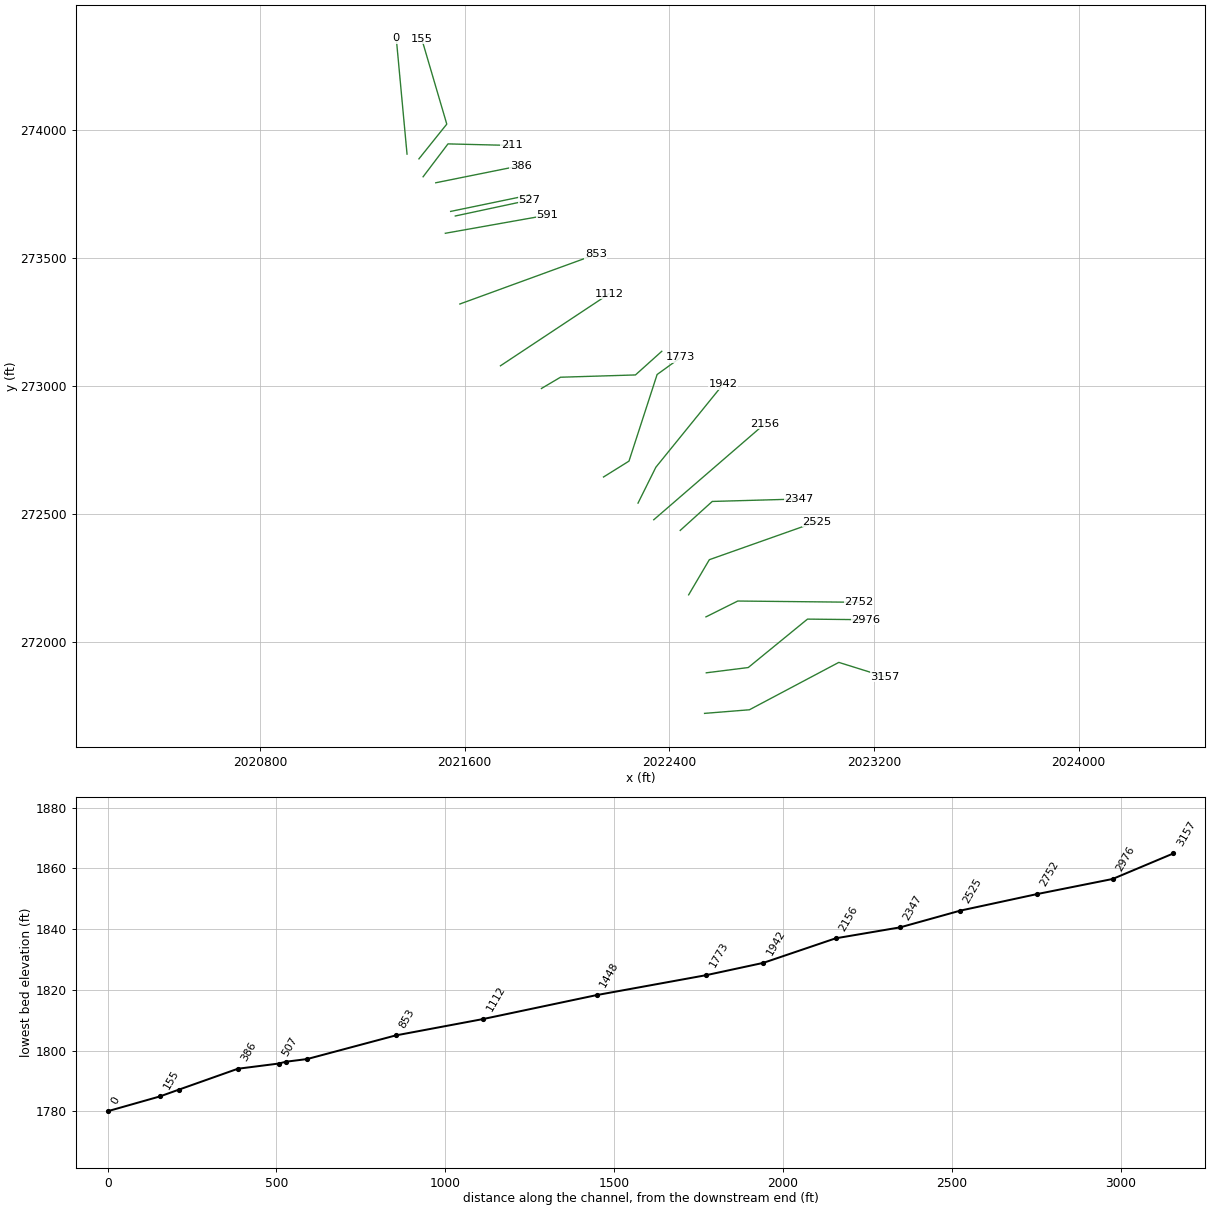
HEC-RAS study LAURELCK_T1.prj: LAURELCK_T1

--- LAURELCK_T1.g01 (geometry) --- (continued)

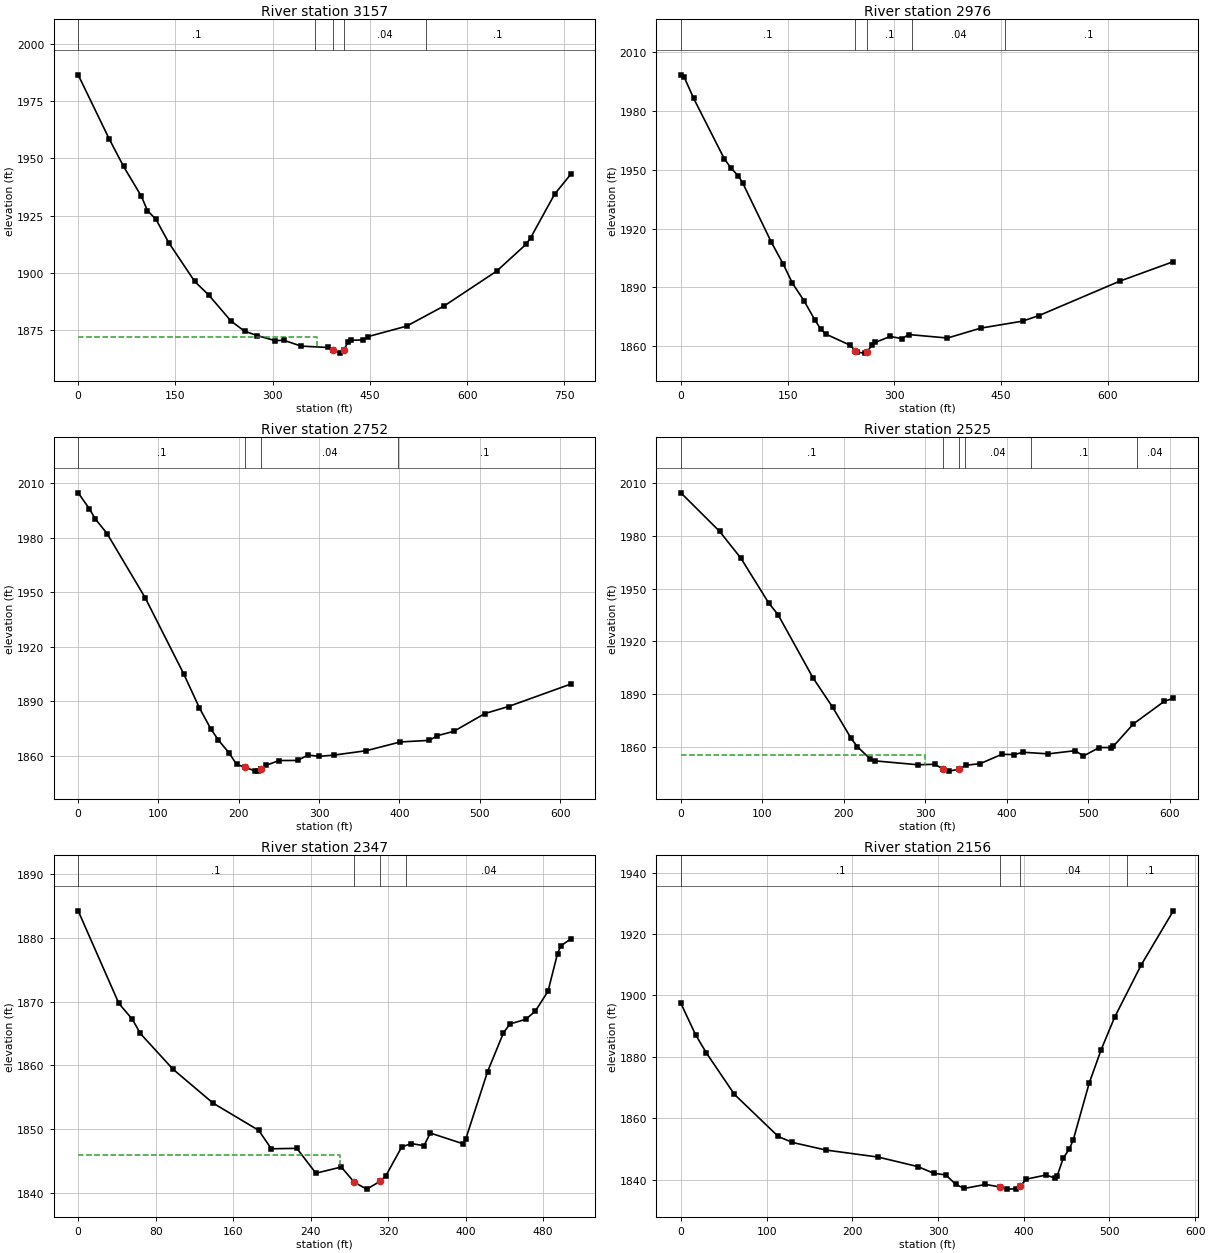
Type RM Length L Ch R = 1 ,3157    ,177,180.3,182.5
XS GIS Cut Line= 4
2022538.03737636271720.388503227 2022713.2608333 271734.46812041
2023062.61472126271919.673174929 2023242.3447387271863.504355888
#Sta/Elev= 30
       0 1986.45    47.6 1958.62      70 1946.47    97.5 1933.42   106.8 1927.21
     120 1923.35   139.7 1913.18   179.7 1896.27     202 1890.13   235.4 1879.05
   256.6 1874.51   276.2 1872.63   303.6 1870.41   317.2 1870.56   343.9 1868.02
   385.2 1867.41   392.5 1866.11   404.6 1864.95   409.5  1866.2   416.7 1869.95
     421 1870.56   438.6  1870.7     447 1872.16   506.5 1876.73   564.8 1885.61
   645.3 1900.71   691.1 1912.54     698 1915.37   734.7 1934.29   759.5 1942.94
#Mann= 5 ,-1 , 0
       0      .1       0  365.79     .04       0   392.5    .045       0
   409.5     .04       0  535.79      .1       0
#XS Ineff= 2 , 0
             368    1872
Permanent Ineff=
       F       F
Bank Sta=392.5,409.5
XS Rating Curve= 0 ,0
Exp/Cntr=0.3,0.1

Type RM Length L Ch R = 1 ,2976    ,232.9,224.5,214.6
XS GIS Cut Line= 4
2022544.69430648 271878.925134432022708.59931182271899.513719342
2022940.20875242272088.7700803362023168.22824839 272086.37829891
#Sta/Elev= 30
       0 1998.43     4.7 1997.21    17.9 1986.43    60.9 1955.69    70.8 1950.69
    80.8 1946.87    87.1 1943.13   127.1 1913.13   143.6  1902.1   156.8  1892.2
   173.1 1883.21   188.4 1873.38   196.8 1868.71   203.4  1866.3   237.5 1860.62
   245.4 1857.78   247.8 1856.99   258.2 1856.52   261.7 1857.15   268.7 1860.66
   273.1 1861.96   294.3 1865.03   311.2 1863.88     320    1866   374.8 1864.22
   421.4 1869.26   480.3 1872.83   503.3 1875.65   617.2 1893.25   692.3 1903.17
#Mann= 5 ,-1 , 0
       0      .1       0   245.4    .045       0   261.7      .1       0
  325.19     .04       0  455.19      .1       0
Bank Sta=245.4,261.7
XS Rating Curve= 0 ,0
Exp/Cntr=0.3,0.1

Type RM Length L Ch R = 1 ,2752    ,220.9,226.7,231.2
XS GIS Cut Line= 3
2022543.42341287272097.5369741832022667.63463625 272159.43744379
2023141.95940752272154.529305364
#Sta/Elev= 30
       0 2004.72      14  1995.9    21.3 1990.38      36 1982.29    83.6 1946.83
   131.3 1905.15   150.9  1886.4   164.9 1874.97   174.7 1868.54   187.8 1861.61
   197.3 1855.22   207.8 1853.68   220.7 1851.53   223.9 1851.56   227.2 1852.64
   227.2 1852.66   233.7 1854.71   250.2 1857.36   273.2 1857.41   286.3 1860.43
   299.4 1859.65   319.1 1860.39   358.5 1862.76   401.1 1867.59   437.2 1868.46
     447 1871.01   467.6 1873.42   506.5 1883.24   535.8  1887.1   613.1 1899.42
#Mann= 4 ,-1 , 0
       0      .1       0   207.8    .045       0   227.2     .04       0
  398.78      .1       0
Bank Sta=207.8,227.2
XS Rating Curve= 0 ,0
Exp/Cntr=0.3,0.1

Type RM Length L Ch R = 1 ,2525    ,181.9,177.7,172.2
XS GIS Cut Line= 3
2022475.76856132272183.6538913872022556.58592225 272320.96284597
 2022976.3071075272469.418904296
#Sta/Elev= 30
       0 2004.59    47.4 1982.71    73.6 1967.39   107.8 1941.84   119.3 1935.16
   162.1 1899.26   186.5 1882.33   208.9 1864.77   216.6 1860.01     232 1853.19
   238.7 1851.91   290.9 1849.72   311.7    1850     322 1847.24   329.2 1846.09
   341.1 1847.18     350 1849.44   367.4 1850.35     394 1855.69   409.2 1855.48
   419.7 1856.85     451 1855.92     484 1857.74   494.2  1854.7   513.6 1859.53
   527.7 1859.51     531  1860.3   555.4 1872.95   593.6 1885.93   604.5 1887.48
#Mann= 6 ,-1 , 0
       0      .1       0     322    .045       0   341.1      .1       0
  349.33     .04       0  429.33      .1       0  559.33     .04       0
#XS Ineff= 2 , 0
             300    1855
Permanent Ineff=
       F       F
Bank Sta=322,341.1
XS Rating Curve= 0 ,0
Exp/Cntr=0.3,0.1

Type RM Length L Ch R = 1 ,2347    ,179.7,191.3,203.5
XS GIS Cut Line= 3
2022442.80230006272435.3730056392022567.97319675272548.600917205
2022907.39890511272558.203280421
#Sta/Elev= 30
       0 1884.26      42 1869.73      56 1867.23    64.1 1865.02    97.8 1859.42
   139.3 1854.08   186.3 1849.82   199.4 1846.92   225.7 1846.99   245.4 1843.09
   271.6 1844.06     285 1841.66   297.9 1840.59   311.5  1841.8   317.6 1842.69
     334  1847.2   343.8 1847.74     357 1847.41   363.5 1849.39   396.8 1847.73
     400 1848.42   422.6 1859.03     439 1865.11   445.6  1866.5     462 1867.24
   471.8  1868.5     485 1871.65   494.8 1877.55   498.1 1878.74   508.3 1879.84
#Mann= 4 ,-1 , 0
       0      .1       0     285    .045       0   311.5      .1       0
  338.78     .04       0
#XS Ineff= 2 , 0
             270    1846
Permanent Ineff=
       F       F
Bank Sta=285,311.5
XS Rating Curve= 0 ,0
Exp/Cntr=0.3,0.1

Type RM Length L Ch R = 1 ,2156    ,208.7,214.3,216.3
XS GIS Cut Line= 2
2022339.51030462272477.1803612482022774.24185159272852.885918417
#Sta/Elev= 30
       0 1897.42    17.2 1887.16    29.8 1881.26    62.4 1867.82   113.6  1854.1
   129.9 1852.18     169  1849.7   230.1  1847.4   276.4 1844.31   295.3  1842.1
     309 1841.61   320.7 1838.53   330.5 1837.18   355.4  1838.5   372.8 1837.64
   380.6 1836.97   390.7 1837.08   395.7 1837.85   403.1 1840.23   425.8 1841.54
   436.9 1840.57   439.2 1841.38   446.2 1847.06   453.2 1850.02   457.8 1852.98
   476.4 1871.44   490.4 1882.37   506.1 1892.89   536.9 1909.82   574.6 1927.53
#Mann= 4 ,-1 , 0
       0      .1       0   372.8    .045       0   395.7     .04       0
     520      .1       0
Bank Sta=372.8,395.7
XS Rating Curve= 0 ,0
Exp/Cntr=0.3,0.1

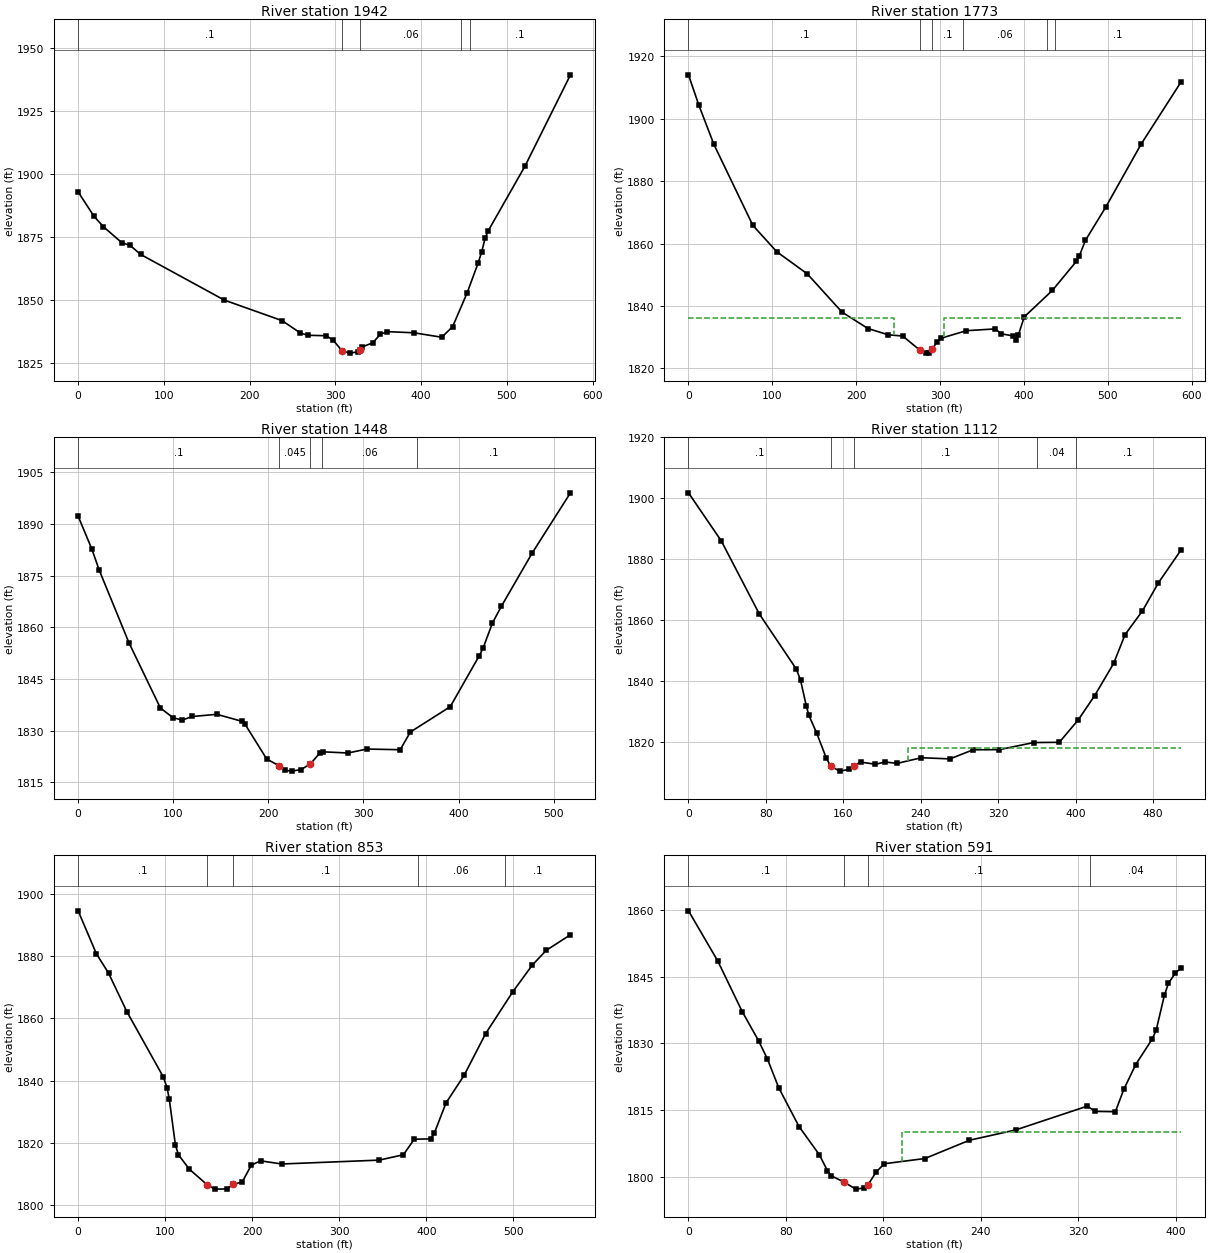
Type RM Length L Ch R = 1 ,1942    ,160.8,168.3,172.2
XS GIS Cut Line= 3
2022277.91571686272542.1449852432022347.60548001272682.337735113
 2022610.7710204273006.762813197
#Sta/Elev= 30
       0 1892.82    18.5 1883.14    29.5 1879.02    50.9  1872.7    60.7 1871.58
    72.9 1868.03   170.6  1849.9   237.8 1841.78   259.3 1836.85   267.8 1835.96
   289.4 1835.78   297.4 1834.06   307.8 1829.82   317.1 1828.88   326.4  1829.4
   328.8 1830.31   331.2 1831.33   343.8 1832.99   352.3 1836.31   360.7  1837.4
   391.7 1836.95   424.1 1835.18   436.8 1839.36   453.7 1852.73   466.4 1864.45
   470.6 1868.89   474.8 1874.52     478 1877.19   521.3 1903.09   574.3 1939.28
#Mann= 5 ,-1 , 0
       0      .1       0   307.8    .045       0   328.8     .06       0
  446.56     .04       0  456.56      .1       0
Bank Sta=307.8,328.8
XS Rating Curve= 0 ,0
Exp/Cntr=0.3,0.1

Type RM Length L Ch R = 1 ,1773    ,345.4,325.1,299.9
XS GIS Cut Line= 4
2022143.06316989272644.1410837432022242.53940191272706.182518797
2022352.46799544273044.6314291542022444.72030354273111.325829034
#Sta/Elev= 30
       0  1914.1    12.2 1904.48    30.3 1891.78    76.7 1865.83   105.2 1857.38
   141.6 1850.27     183 1838.01     214 1832.73   238.2 1830.73   255.4 1830.33
   276.1 1825.73     283 1824.85   286.5  1824.9   290.6 1826.02   295.8  1828.3
     301 1829.62   331.3 1832.05   365.8 1832.62   372.7 1831.06   386.5 1830.39
     390 1828.95   393.4  1830.8   400.3 1836.48   433.8 1844.96   462.5 1854.31
   465.9 1855.99   473.1 1860.97   497.5  1871.7   539.7 1891.92   586.9 1911.69
#Mann= 6 ,-1 , 0
       0      .1       0   276.1    .045       0   290.6      .1       0
  327.24     .06       0  427.24     .04       0  437.24      .1       0
#XS Ineff= 2 , 0
             245    1836     305            1836
Permanent Ineff=
       F       F
Bank Sta=276.1,290.6
XS Rating Curve= 0 ,0
Exp/Cntr=0.3,0.1

Type RM Length L Ch R = 1 ,1448    ,320,336.6,350.6
XS GIS Cut Line= 4
2021900.51578595272990.0844745262021975.03073496273034.048294442
2022267.87448457273042.9900883232022370.70511421273135.388625096
#Sta/Elev= 30
       0 1892.22    14.4  1882.7      22 1876.68    53.4 1855.52    86.5 1836.57
    99.9 1833.75   109.4 1833.09   120.1 1834.12   145.8 1834.75   172.1 1832.74
   175.3 1831.96   198.3 1821.78   211.4 1819.81     218  1818.5   224.6 1818.27
   234.4 1818.73   244.3 1820.37   254.1 1823.53   257.4 1823.87   283.7 1823.53
   303.7 1824.68   338.7 1824.48   349.3 1829.61   391.3 1836.97   421.8 1851.76
   425.7 1853.89   435.7 1861.28     445 1866.07   477.5 1881.57   517.7 1899.01
#Mann= 5 ,-1 , 0
       0      .1       0   211.4    .045       0   244.3      .1       0
  256.52     .06       0  356.52      .1       0
Bank Sta=211.4,244.3
XS Rating Curve= 0 ,0
Exp/Cntr(USF)=0,0
Exp/Cntr=0.3,0.1

Type RM Length L Ch R = 1 ,1112    ,262.3,258.9,252.9
XS GIS Cut Line= 2
2021740.30864558273078.7572638482022164.29870545273359.678621617
#Sta/Elev= 30
       0 1901.73    33.9 1885.94    73.2 1861.94   111.5 1843.83   115.8 1840.18
   121.8 1831.67   124.4 1828.65   132.3 1822.99   142.3  1814.7     147 1811.93
   156.5 1810.37     166 1810.97   170.7 1812.11   177.8 1813.34   193.1 1812.63
   203.1 1813.36   215.7 1812.92   240.6 1814.77   270.1 1814.39     294 1817.37
   321.2 1817.43   356.6 1819.75   383.1 1819.83   402.7 1827.21   419.6 1835.15
   439.2 1845.72     451 1855.17     469 1862.98   485.5  1872.2   508.6 1882.85
#Mann= 5 ,-1 , 0
       0      .1       0     147    .045       0   170.7      .1       0
     360     .04       0     400      .1       0
#XS Ineff= 2 , 0
                             227            1818
Permanent Ineff=
       F       F
Bank Sta=147,170.7
XS Rating Curve= 0 ,0
Exp/Cntr(USF)=0,0
Exp/Cntr=0.3,0.1

Type RM Length L Ch R = 1 ,853     ,263.7,261.7,258.3
XS GIS Cut Line= 2
2021581.59180419273320.1856986422022112.88339063273513.924566069
#Sta/Elev= 30
       0 1894.72    20.9  1880.9    34.9 1874.63      56 1862.18    97.7  1841.2
   102.1  1837.7   104.7 1833.94   111.7 1819.22   115.2 1816.05   127.7  1811.4
   148.2 1806.37   157.1 1804.97     171 1805.02     178 1806.47   188.5 1807.31
     199 1812.74   209.5 1814.09   233.9 1813.08   345.7 1814.32   373.6 1816.06
   386.1 1821.08     405 1821.17   409.2 1823.08   422.5 1832.75   443.4  1841.7
     468  1855.1   499.3 1868.64   521.8 1877.27   537.7 1881.98   565.5 1887.01
#Mann= 5 ,-1 , 0
       0      .1       0   148.2    .045       0     178      .1       0
     390     .06       0     490      .1       0
Bank Sta=148.2,178
XS Rating Curve= 0 ,0
Exp/Cntr(USF)=0,0
Exp/Cntr=0.3,0.1

Type RM Length L Ch R = 1 ,591     ,62.9,63.8,63.8
XS GIS Cut Line= 2
2021524.96044294 273596.636159472021922.87027065 273667.42536103
#Sta/Elev= 30
       0 1859.85    24.1 1848.53    44.1 1837.17    57.5 1830.63    64.8  1826.5
    74.1 1820.02    90.8 1811.27   107.4 1804.96   114.1 1801.34   117.4 1800.18
   127.4 1798.82   137.4  1797.2     144 1797.46   147.4 1798.18   154.1 1801.07
   160.8 1802.92   194.1 1804.09   230.7 1808.21   268.5 1810.51   327.4 1815.88
     334  1814.7   350.5 1814.63   357.4 1819.65   367.2 1825.25   380.7 1830.98
     384 1833.01   390.7  1840.8     394 1843.52   399.6 1845.79   404.2 1846.94
#Mann= 4 ,-1 , 0
       0      .1       0   127.4    .045       0   147.4      .1       0
     330     .04       0
#XS Ineff= 2 , 0
                             175            1810
Permanent Ineff=
       F       F
Bank Sta=127.4,147.4
XS Rating Curve= 0 ,0
Exp/Cntr(USF)=0,0
Exp/Cntr=0.5,0.3

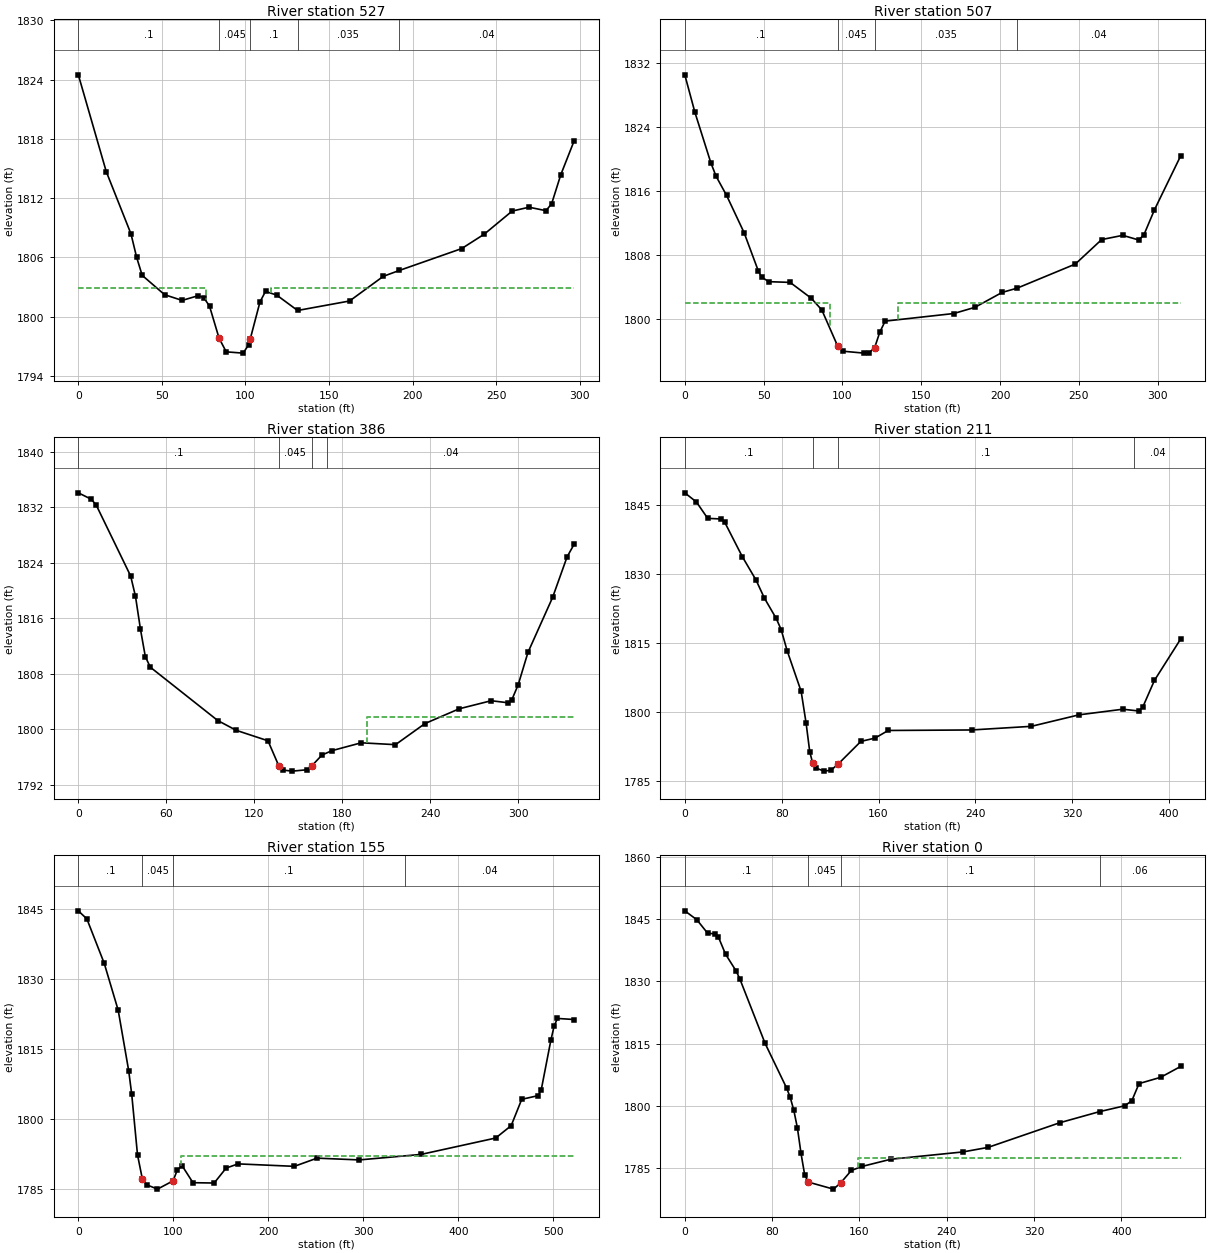
Type RM Length L Ch R = 1 ,527     ,20.7,20.6,20.8
XS GIS Cut Line= 2
2021563.85255236273664.1864487462021854.01103171273726.225108793
#Sta/Elev= 30
       0 1824.49    16.7 1814.69    31.5 1808.38    34.9    1806    38.2 1804.18
    51.6 1802.22    62.1 1801.64    71.8 1802.12    75.1 1801.91    78.5 1801.06
    84.2 1797.82    88.5 1796.43    98.6  1796.3     102 1797.16   102.91797.749
   108.7 1801.49     112 1802.55   118.7 1802.18   131.2 1800.62   162.3 1801.58
   182.5 1804.08     192 1804.67   229.4 1806.89   242.9 1808.35   259.6 1810.69
   269.7 1811.08   279.8 1810.73   283.2 1811.42   288.7 1814.37   296.7 1817.81
#Mann= 5 ,-1 , 0
       0      .1       0    84.2    .045       0   102.9      .1       0
   131.2    .035       0     192     .04       0
#XS Ineff= 3 ,-1
       0    76.2  1802.9   110.9     115  1800.5     115  296.72  1802.9
Permanent Ineff=
       F       F       F
Bank Sta=84.2,102.9
XS Rating Curve= 0 ,0
Exp/Cntr(USF)=0,0
Exp/Cntr=0.5,0.3

Type RM Length L Ch R = 1 ,507     ,121.2,121.1,121
XS GIS Cut Line= 2
2021545.69419164273682.0561232772021853.63573967273745.855769021
#Sta/Elev= 30
       0 1830.49     6.4 1825.81    16.5 1819.51    19.8 1817.83    26.5 1815.42
    37.6 1810.77    46.6    1806    48.7 1805.21    53.3 1804.64    66.8 1804.55
    80.2 1802.57    86.9 1801.11    96.9 1796.62   100.3 1795.95   113.7 1795.71
     117 1795.77   120.4 1796.38   123.7 1798.34   127.1 1799.71   170.6 1800.66
     184 1801.43   201.3  1803.3   210.8 1803.83   247.7 1806.84   264.4  1809.9
   277.8 1810.43   287.9 1809.85   291.2 1810.49   297.9 1813.62   314.5 1820.35
#Mann= 4 ,-1 , 0
       0      .1       0    96.9    .045       0   120.4    .035       0
   210.8     .04       0
#XS Ineff= 3 ,-1
       0    91.9    1802   126.4     135  1799.3     135 334.595    1802
Permanent Ineff=
       F       F       F
Bank Sta=96.9,120.4
XS Rating Curve= 0 ,0
Exp/Cntr(USF)=0,0
Exp/Cntr=0.5,0.3

Type RM Length L Ch R = 1 ,386     ,163.9,174.8,186.9
XS GIS Cut Line= 2
2021487.50405875 273794.019834252021819.10128099273860.860112011
#Sta/Elev= 30
       0 1834.08     8.8 1833.16    12.2 1832.32    35.7  1822.1      39 1819.16
    42.4 1814.42    45.7  1810.5    49.1 1808.97    95.1 1801.29   107.7 1799.88
   129.4 1798.37   136.9  1794.7   139.4 1794.15   146.1    1794   156.2  1794.2
   159.2 1794.74   166.2 1796.31   172.9 1796.94     193 1798.08   216.4 1797.81
   236.5 1800.85   259.9 1802.98   281.7 1804.14   293.4 1803.84   295.7 1804.24
   300.1 1806.43   306.8 1811.11   323.6 1819.02   333.5 1824.87   338.3 1826.68
#Mann= 4 ,-1 , 0
       0      .1       0   136.9    .045       0   159.2      .1       0
     170     .04       0
#XS Ineff= 2 , 0
                          196.89         1801.84
Permanent Ineff=
       F       F
Bank Sta=136.9,159.2
XS Rating Curve= 0 ,0
Exp/Cntr(USF)=0,0
Exp/Cntr=0.3,0.1

Type RM Length L Ch R = 1 ,211     ,55.1,56,57.5
XS GIS Cut Line= 3
2021438.02489206 273817.457334252021535.24711433273945.929556459
 2021783.5110032273939.853167579
#Sta/Elev= 30
       0 1847.62     9.6 1845.63    18.9 1842.07    30.2 1841.93      33 1841.21
    47.5 1833.74    58.8 1828.67    65.8  1824.7    75.5 1820.31    79.6 1817.87
    84.5 1813.31    96.1 1804.44   100.2 1797.52   103.2 1791.31   105.6 1788.87
   108.4 1787.77     115 1787.11   120.7  1787.3   126.7 1788.66   145.4 1793.57
   157.1 1794.29     168 1795.95   236.9 1796.06   286.2 1796.85   325.6 1799.35
   361.7 1800.57   374.8 1800.19   378.1 1800.95   387.9 1806.85   409.5 1815.82
#Mann= 4 ,-1 , 0
       0      .1       0   105.6    .045       0   126.7      .1       0
  371.11     .04       0
Bank Sta=105.6,126.7
XS Rating Curve= 0 ,0
Exp/Cntr(USF)=0,0
Exp/Cntr=0.3,0.1

Type RM Length L Ch R = 1 ,155     ,129.7,154.8,163.2
XS GIS Cut Line= 3
2021421.70786992273887.5203465752021530.53973408274023.182543456
 2021432.4192868274357.093841403
#Sta/Elev= 30
       0 1844.62       9 1842.88    27.3 1833.33      42 1823.25      53 1810.32
    56.2 1805.25    62.3 1792.24    67.3 1787.16    71.9 1785.82    83.3 1784.88
    99.7 1786.65   104.3 1789.03   109.3 1789.89   120.7 1786.26     143 1786.19
   155.6  1789.4   168.2  1790.3   227.4 1789.77   251.3 1791.53   295.8 1791.15
   360.8 1792.33   439.4 1795.85   455.7 1798.51   466.8 1804.16   483.9 1804.94
   487.3 1806.15   497.5 1816.87     501 1819.95   504.4 1821.52     522 1821.29
#Mann= 4 ,-1 , 0
       0      .1       0    67.3    .045       0    99.7      .1       0
  343.92     .04       0
#XS Ineff= 2 , 0
                          108.51            1792
Permanent Ineff=
       F       F
Bank Sta=67.3,99.7
XS Rating Curve= 0 ,0
Exp/Cntr(USF)=0,0
Exp/Cntr=0.3,0.1

Type RM Length L Ch R = 1 ,0       ,,,
XS GIS Cut Line= 2
2021375.17812102273906.1103895062021333.14589584274358.440150179
#Sta/Elev= 30
       0 1846.98      11 1844.84    20.8 1841.63    27.4 1841.41    30.7 1840.73
    37.3 1836.56    47.2 1832.43    50.5 1830.54    73.6 1815.06    93.3 1804.32
    96.6 1802.08    99.9 1798.95   103.2 1794.69   106.5 1788.58   109.8  1783.5
   113.1  1781.7   136.2    1780   142.8 1781.49   152.6 1784.49   162.5 1785.47
   188.9  1787.2   254.8 1788.95   277.8 1790.04   343.7 1795.99     380 1798.65
   403.1 1800.06   409.6 1801.28   416.2  1805.4     436 1806.91   454.3 1809.52
#Mann= 4 ,-1 , 0
       0      .1       0   113.1    .045       0   142.8      .1       0
     380     .06       0
#XS Ineff= 2 , 0
                             159          1787.5
Permanent Ineff=
       F       F
Bank Sta=113.1,142.8
XS Rating Curve= 0 ,0
Exp/Cntr(USF)=0,0
Exp/Cntr=0.3,0.1
LCMann Table=0

Chan Stop Cuts=-1
Use User Specified Reach Order=0
Composite Channel Slope=5